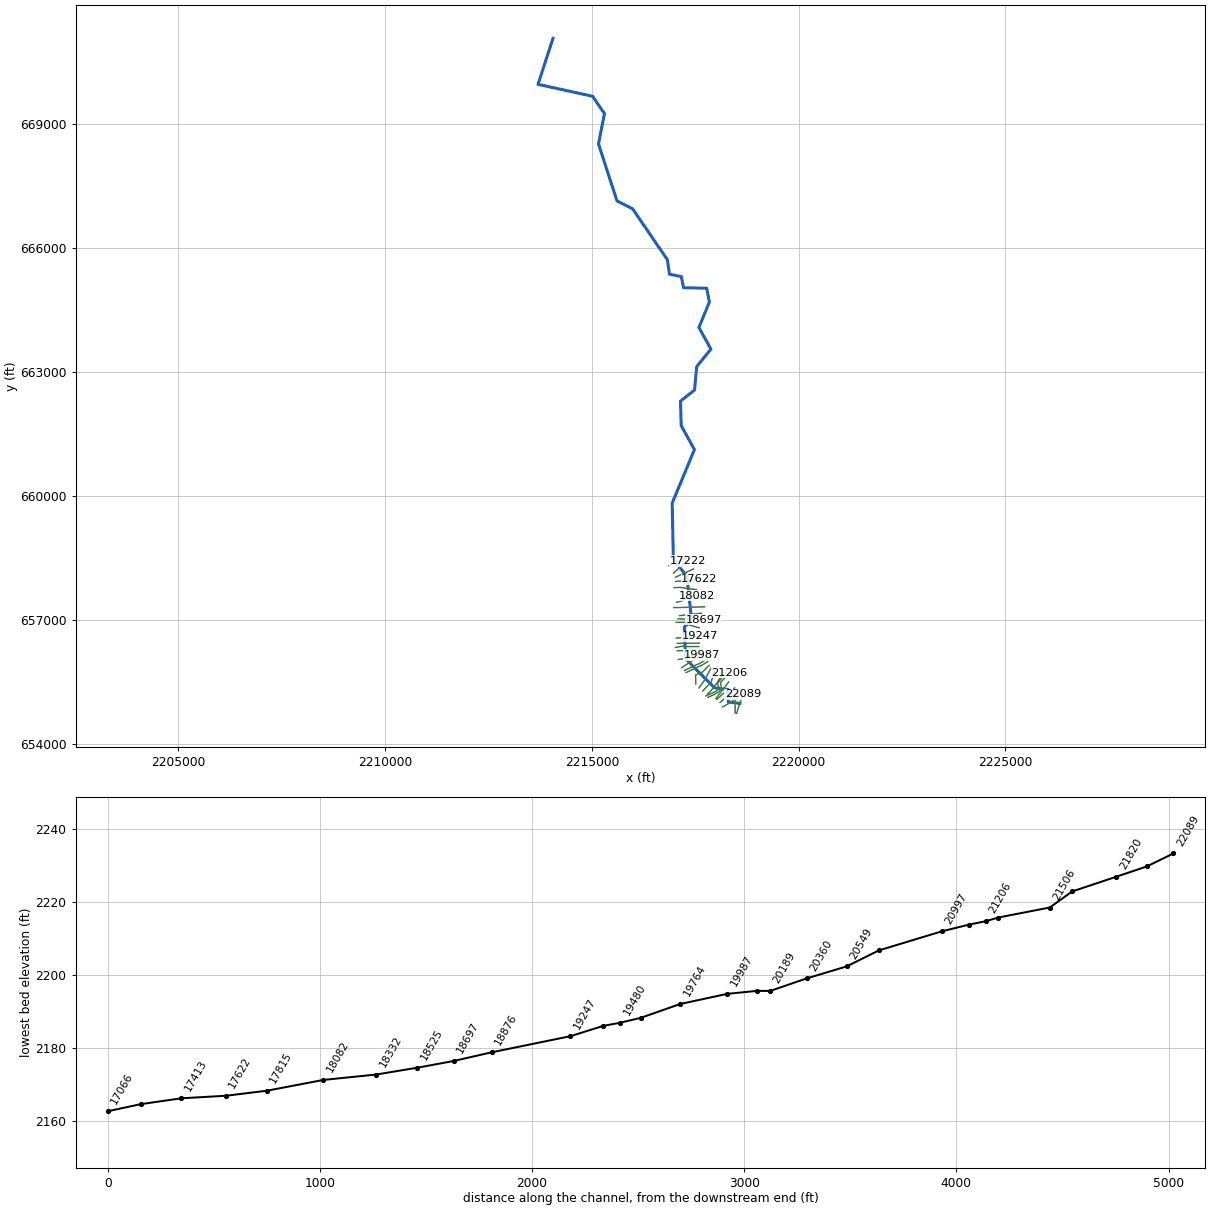
--- JENKSFK.prj (project) ---

Proj Title=JENKSFK
Current Plan=p01
Default Exp/Contr=0,0
English Units
Geom File=g01
Flow File=f01
Plan File=p01
BEGIN DESCRIPTION:
-------- MODELED AS PART OF WVEMD CTP PROGRAM, 2023----------
Stream Name: Jenks Fork
Flood Zone:  AFH
Upshur County, WV
HEC-RAS Version: RAS 6.3
Vertical Datum: NAVD88
Projection: NAD 1983 StatePlane West Virginia S FIPS 4702 (US Feet)
Terrain: 1-meter LIDAR (FEMA Region III 3DEP collected 2016-2018)
Land Use: 2019 NLCD
Hydrologic Method:
WV SIR2010-5033 regression equations
Additional Model Notes:
None
END DESCRIPTION:
DSS Export Rating Curves= 0
DSS Export Rating Curve Sorted= 0
DSS Export Volume Flow Curves= 0
DXF OffsetX= 0
DXF OffsetY= 0
DXF ScaleX= 0
DXF ScaleY= 0

--- JENKSFK.p01 (plan) ---

Plan Title=Floodplain
Program Version=6.31
Short Identifier=Floodplain
Geom File=g01
Flow File=f01
Subcritical Flow
K Sum by GR= 0
Std Step Tol= 0.01
Critical Tol= 0.01
Num of Std Step Trials= 20
Max Error Tol= 0.3
Flow Tol Ratio= 0.001
Split Flow NTrial= 30
Split Flow Tol= 0.02
Split Flow Ratio= 0.02
Log Output Level= 0
Friction Slope Method= 1
Unsteady Friction Slope Method= 2
Unsteady Bridges Friction Slope Method= 1
Parabolic Critical Depth
Global Vel Dist= 0 , 0 , 0
Global Log Level= 0
CheckData=True
Encroach Param=-1 ,0,0, 0
Mapping Interval=1HOUR
Computation Time Step Use Courant=        0
Computation Time Step Use Time Series=    0
Computation Time Step Count To Double=0
Computation Time Step Max Doubling=0
Computation Time Step Max Halving=0
Computation Time Step Residence Courant=0
Run HTab= 0
Run UNet= 0
Run Sediment= 0
Run PostProcess= 0
Run WQNet= 0
Run RASMapper=-1
UNET Theta= 0
UNET Theta Warmup= 0
UNET ZTol= 0
UNET ZSATol= 0
UNET MxIter= 0
UNET Max Iter WO Improvement= 0
UNET MaxInSteps= 0
UNET DtIC= 0
UNET DtMin= 0
UNET MaxCRTS= 0
UNET WFStab= 0
UNET SFStab= 0
UNET WFX= 1
UNET SFX= 1
UNET Gravity=32.17405
UNET 1D Methodology=Finite Difference
UNET DSS MLevel= 1
UNET Pardiso=0
UNET DZMax Abort= 0
UNET Use Existing IB Tables= 0
UNET Froude Reduction=False
UNET Froude Limit= 0
UNET Froude Power= 0
UNET D1 Cores= 0
UNET WindReference=Eulerian
UNET WindDragFormulation=Hsu (1988)
UNET D2 Coriolis=0
UNET D2 Cores= 0
UNET D2 Theta= 1
UNET D2 Theta Warmup= 1
UNET D2 Z Tol= 0.01
UNET D2 Volume Tol= 0.01
UNET D2 Max Iterations= 20
UNET D2 Equation= 0
UNET D2 RampUpFraction=0.1
UNET D2 TimeSlices= 1
UNET D2 Turbulence Formulation=Non-Conservative (original)
UNET D2 Eddy Viscosity=0.3
UNET D2 Transverse Eddy Viscosity=0.1
UNET D2 Smagorinsky Mixing=0
UNET D2 BCVolumeCheck=0
UNET D2 Cores=0
UNET D2 SolverType=PARDISO (Direct)
UNET D2 Minimum Iterations= 3
UNET D2 Maximum Iterations= 30
UNET D2 Restart Number= 10
UNET D2 Relaxation Coeff=1.3
UNET D2 SOR Precondition Iterations= 10
UNET D2 ILUT Maximum Fill= 8
UNET D2 ILUT Tolerance=1E-08
UNET D2 Convergence Tolerance=0.00001
UNET D1D2 MaxIter= 0
UNET D1D2 ZTol=0.01
UNET D1D2 QTol=0.1
UNET D1D2 MinQTol=1
Write IC File= 0
Write IC File at Fixed DateTime=0
Write IC File at Sim End=0
Echo Input=False
Echo Parameters=False
Echo Output=False
Write Detailed= 0
HDF Write Warmup=0
HDF Write Time Slices=0
HDF Flush=0
HDF Compression= 1
HDF Chunk Size= 1
HDF Spatial Parts= 1
HDF Use Max Rows=0
HDF Fixed Rows= 1
Calibration Method= 0
Calibration Iterations= 20
Calibration Max Change=0.05
Calibration Tolerance=0.2
Calibration Maximum=1.5
Calibration Minimum=0.5
Calibration Optimization Method= 1
WQ AD Non Conservative
WQ ULTIMATE=-1
WQ Max Comp Step=1HOUR
WQ Output Interval=15MIN
WQ Output Selected Increments= 0
WQ Create Restart=0
WQ Fixed Restart=0
WQ System Summary=0
WQ Write To DSS=0
Sorting and Armoring Iterations= 10
XS Update Threshold= 0.02
Bed Roughness Predictor= 0
Hydraulics Update Threshold= 0.02
Energy Slope Method= 1
Volume Change Method= 1
Sediment Retention Method= 0
Sediment TS Multiplier= 1
Warm Up Method= 0
XS Weighting Method= 0
Number of US Weighted Cross Sections= 1
Number of DS Weighted Cross Sections= 1
Upstream XS Weight=0
Main XS Weight=1
Downstream XS Weight=0
Number of DS XS's Weighted with US Boundary= 1
Upstream Boundary Weight= 1
Weight of XSs Associated with US Boundary= 0
Number of US XS's Weighted with DS Boundary= 1
Downstream Boundary Weight= 0.5
Weight of XSs Associated with DS Boundary= 0.5
Percentile Method= 0
Sediment Output Level= 3
Mass or Volume Output= 0
Output Increment Type= 1
Profile and TS Output Increment= 1
Transport Output Increment 1
XS Output Flag= 0
XS Output Increment= 10
Read HDF5 Sediment Hotstart= 0
Sediment Hotstart Type= 0
Write Gradation File= 0
Read Gradation Hotstart= 0
Write HDF5 File= 1
Write Binary Output= 1
Write DSS Sediment File= 0
DSS Sediment Output Type= 1
SV Curve= 0
Specific Gage Flag= 0
Subcell Erosion Methods= 0
Subcell Deposition Methods= 0
Advection Scheme= 1
Matrix Solver= 0
Implicit Weighting Factor= 1
Maximum Outer Loop Convergence Iterations= 5
Convergence Maximum Absolute= 0.001
Convergence RMSE= 0.0001
Grain Fractions Max Abs Error= 0.001
Max Subgrid Regions= 1
Max Subgrid Length Scale= 3.402823E+38
Initial Layer Thickness= 3.402823E+38
Min Layer Thickness= 3.402823E+38
Max Layer Thickness= 3.402823E+38
Number of Layers= 5

--- JENKSFK.f01 (steady flow) ---

Flow Title=Flows
Program Version=6.31
Number of Profiles= 1
Profile Names=01pct
River Rch & RM=JENKSFK,Main,22089
     482
River Rch & RM=JENKSFK,Main,19987
     631
River Rch & RM=JENKSFK,Main,18525
     745
River Rch & RM=JENKSFK,Main,15482
     889
River Rch & RM=JENKSFK,Main,10954
    1020
River Rch & RM=JENKSFK,Main,10135
    1350
Boundary for River Rch & Prof#=JENKSFK,Main            , 1
Up Type= 0
Dn Type= 3
Dn Slope=0.01924
DSS Import GetInterval= 0
DSS Import GetPeak= 0
DSS Import FillOption= 0

--- JENKSFK.g01 (geometry) ---

Geom Title=Geometry
Program Version=6.31

River Reach=JENKSFK         ,Main
Reach XY= 30
2218579.32700001654978.8620000032218297.25500003655013.030000016
2218288.58400001655317.2790000142217966.53499998655355.768000007
2217264.00300002656059.7310000212217234.44199999656825.018999994
2217408.60200001657007.7919999962217295.22300002658059.930999994
2216969.14000002658460.2740000042216940.32300003659826.249000013
2217478.71200003661122.657000005      2217157.75661701.567000017
2217142.24000002662294.9850000142217480.34299999662563.092000008
2217533.48300001663131.0410000092217877.96800001663552.790000007
2217586.73900002664075.6400000012217839.79300003664692.237000003
2217775.86400002665026.3330000192217215.81300001665039.238999993
2217161.61400001      665308.1472216874.79099998665365.237000003
      2216823.11665717.819999993     2215981.846666949.040000007
2215604.76800001      667140.9412215158.03700003668518.734999999
2215302.69299999669252.1149999952215016.27200003669671.632000014
2213695.51100004669960.628000006  2214057.679735671073.834422931

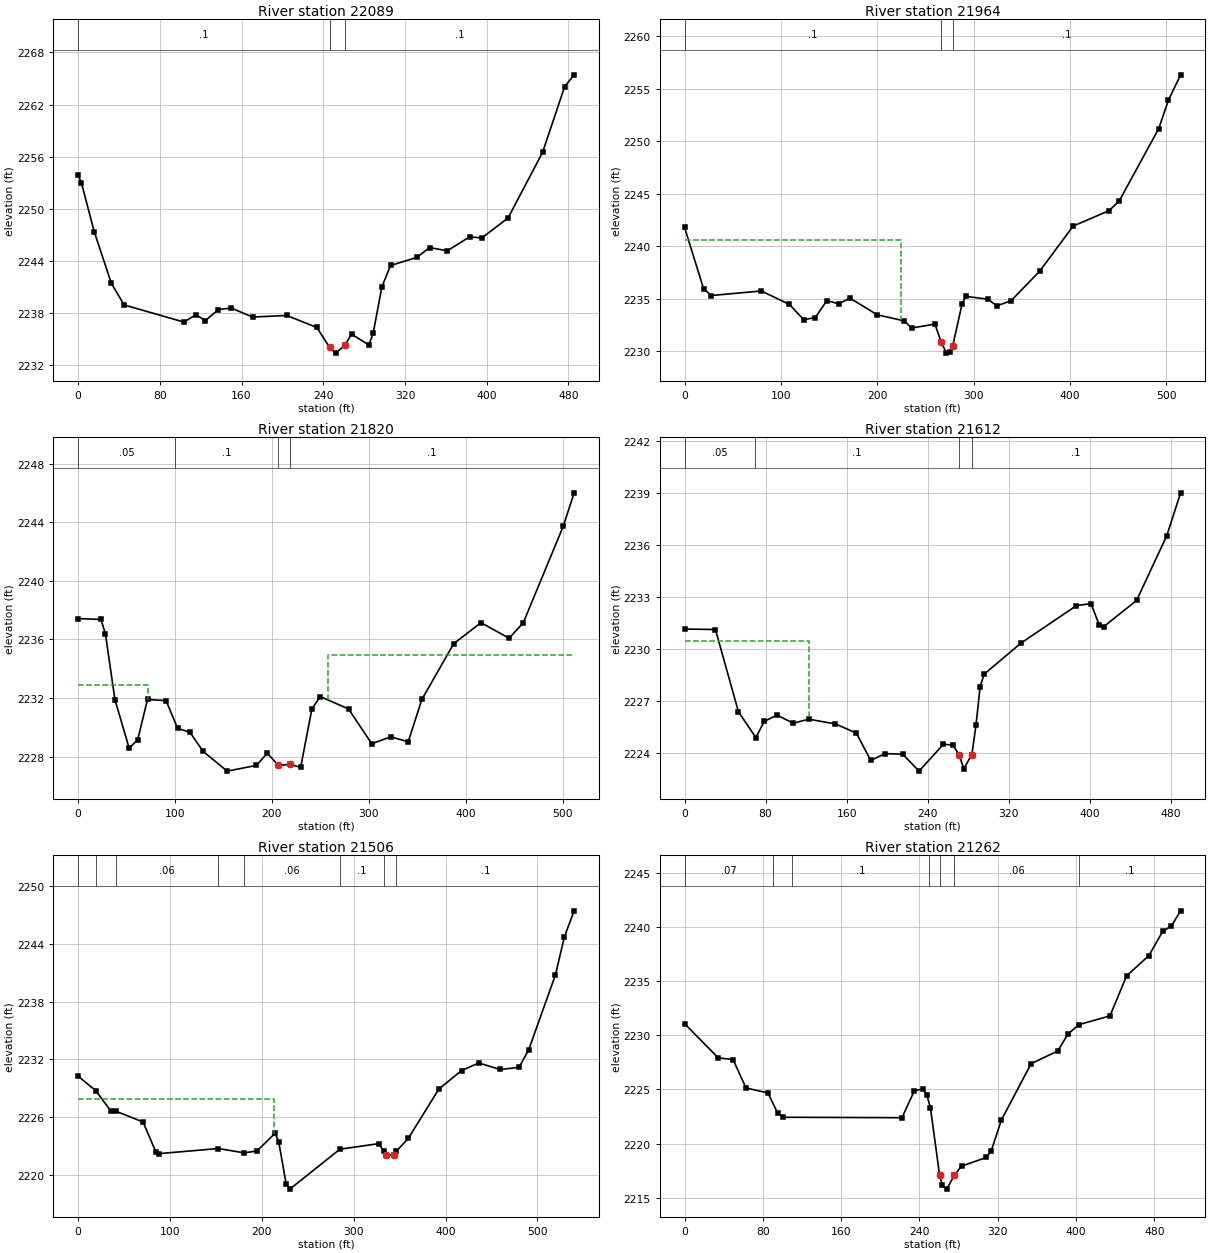
Type RM Length L Ch R = 1 ,22089   ,121.6,124.9,126.7
XS GIS Cut Line= 4
2218499.04938154654738.1331437412218567.93539692654959.136763083
2218604.33049873655060.1945928222218654.79390244655197.892305664
#Sta/Elev= 30
       0 2253.89     3.2 2253.02    15.8 2247.38    32.5 2241.45    45.1 2238.95
   103.7 2236.98   115.1 2237.82   124.7 2237.16   137.3 2238.42   149.8  2238.6
   170.8 2237.56   204.3 2237.74   233.7 2236.36   246.2 2234.07     252 2233.41
     2612234.289   267.7 2235.59   284.7 2234.35   288.9 2235.72   297.4 2241.03
   305.9 2243.49   331.4 2244.41   344.2 2245.55   361.4 2245.18   383.2 2246.78
   395.3 2246.66   420.9 2248.96   454.7  2256.5   476.3 2264.06   485.6 2265.42
#Mann= 3 ,-1,0
       0      .1       0   246.2    .045       0     261      .1       0
Bank Sta=246.2,261
XS Rating Curve= 0 ,0
Exp/Cntr=0.3,0.1

Type RM Length L Ch R = 1 ,21964   ,154.9,143.9,131.6
XS GIS Cut Line= 4
2218461.29997755654745.5110894882218464.59222222654956.168834141
2218456.66002048655047.8287108732218581.70608408655219.383955762
#Sta/Elev= 30
       0 2241.79    19.7 2235.98    27.7 2235.32    79.7 2235.75   108.9 2234.47
   123.7 2233.02   135.7 2233.22   147.7 2234.83   160.1 2234.54   171.7 2235.07
   199.9 2233.49   227.8 2232.91   235.8 2232.23   259.9  2232.6   266.42230.893
   271.9 2229.84   275.9  2229.9   278.32230.485     288 2234.47     292 2235.24
   314.8 2234.97   324.2 2234.34     339 2234.82   369.2 2237.69   403.5 2241.93
   440.7 2243.39   451.3 2244.32   492.3  2251.2   502.3 2253.89     515 2256.31
#Mann= 3 ,-1,0
       0      .1       0   266.4    .045       0   278.3      .1       0
#XS Ineff= 2 , 0
          224.74 2240.63
Permanent Ineff=
       T       F
Bank Sta=266.4,278.3
XS Rating Curve= 0 ,0
Exp/Cntr=0.3,0.1

Type RM Length L Ch R = 1 ,21820   ,212.3,208.7,201
XS GIS Cut Line= 4
2218159.68675578654893.8681177672218247.84709582654943.872761865
2218386.13686506655020.0574460582218518.90250746655234.839038696
#Sta/Elev= 30
       0 2237.42    23.6 2237.36    28.2 2236.37      38 2231.89    52.7 2228.57
    61.5 2229.16    71.6  2231.9    90.8 2231.82   102.6 2229.93   115.4 2229.66
   128.9 2228.36   153.8 2227.01   183.9  2227.4   195.2 2228.23   206.72227.407
   218.82227.466   229.6 2227.27   241.2 2231.26   249.8  2232.1     279 2231.25
   302.9 2228.88   322.6 2229.35   340.5 2229.01   354.6  2231.9   387.5 2235.71
   415.6 2237.14   444.6 2236.08   459.2 2237.13   500.4 2243.71   511.7    2246
#Mann= 4 ,-1,0
       0     .05       0     100      .1       0   206.7    .045       0
   218.8      .1       0
#XS Ineff= 2 , 0
           72.32 2232.88  257.56         2234.91
Permanent Ineff=
       T       F
Bank Sta=206.7,218.8
XS Rating Curve= 0 ,0
Exp/Cntr=0.3,0.1

Type RM Length L Ch R = 1 ,21612   ,103.1,105.4,108.3
XS GIS Cut Line= 4
2218098.27346717655004.1646654062218259.63466835 655139.86772506
2218361.69705355655129.6044684482218487.10591857655253.608347181
#Sta/Elev= 30
       0 2231.16    30.5 2231.13    53.2 2226.38    70.4 2224.89    78.7 2225.82
    91.3 2226.19   107.2 2225.72   122.7 2225.95   148.8 2225.68   169.6 2225.15
   183.8 2223.57     198 2223.96   215.4 2223.93   231.5 2222.95   255.6  2224.5
   264.9 2224.46     271 2223.91   275.7 2223.09   283.7 2223.91   287.8 2225.63
   291.8 2227.82   295.8 2228.55   331.8 2230.33   386.8 2232.51   401.3 2232.63
   409.5 2231.39   413.9  2231.3   446.3 2232.81   476.1 2236.55   489.8 2239.03
#Mann= 4 ,-1,0
       0     .05       0      70      .1       0     271    .045       0
   283.7      .1       0
#XS Ineff= 2 , 0
          122.39 2230.44
Permanent Ineff=
       T       F
Bank Sta=271,283.7
XS Rating Curve= 0 ,0
Exp/Cntr=0.3,0.1

Type RM Length L Ch R = 1 ,21506   ,233.8,243.7,247.1
XS GIS Cut Line= 5
2218022.10208282655075.387517113 2218174.0282376655217.814149941
2218179.61436724655218.2057151152218354.65991057655240.442771108
2218451.02048655655355.049136615
#Sta/Elev= 30
       0 2230.26    19.3 2228.75    35.7 2226.64    41.2 2226.62    70.7 2225.51
    84.8 2222.36    87.6 2222.22   152.7 2222.75     181  2222.3   194.7  2222.5
   214.4 2224.33   218.4 2223.45   226.5 2219.08   230.5 2218.54     285 2222.68
   327.3 2223.26   332.7 2222.47  334.68 2222.07   343.4 2222.07  346.48 2222.48
   359.6 2223.82   392.7 2228.92   417.4 2230.84   436.2 2231.63   459.2 2230.95
   480.1 2231.17   490.6 2233.02   519.7 2240.78   529.4 2244.72     540 2247.41
#Mann= 8 ,-1,0
       0     .05       0    19.3     .07       0    41.2     .06       0
   152.7      .1       0     181     .06       0     285      .1       0
   332.7    .045       0  346.48      .1       0
#XS Ineff= 2 , 0
          213.28 2227.94
Permanent Ineff=
       T       F
Bank Sta=334.68,343.4
XS Rating Curve= 0 ,0
Exp/Cntr=0.3,0.1

Type RM Length L Ch R = 1 ,21262   ,53.3,56,61.5
XS GIS Cut Line= 3
2217997.55851393655098.0492264162218245.55463757655415.703856531
2218307.54418421655499.151323165
#Sta/Elev= 30
       0 2231.09    34.4 2227.93    49.6 2227.76    62.8 2225.14    85.2 2224.68
    95.3 2222.78     101 2222.43   222.2 2222.39   234.9  2224.9   243.5 2225.04
   247.6  2224.5   251.3 2223.27   260.6 2217.08   263.4 2216.12   267.9 2215.78
  275.72 2217.07   283.1 2217.91   308.4 2218.71   313.5 2219.35   323.7 2222.16
   354.1 2227.39   381.3 2228.56   391.7 2230.12     403    2231   434.7 2231.81
   451.7 2235.51   474.5 2237.39   488.8 2239.66   497.4 2240.12   506.9 2241.53
#Mann= 7 ,-1,0
       0     .07       0      90     .06       0     110      .1       0
     250     .06       0   260.6    .045       0  275.72     .06       0
     403      .1       0
Bank Sta=260.6,275.72
XS Rating Curve= 0 ,0
Exp/Cntr=0.3,0.1

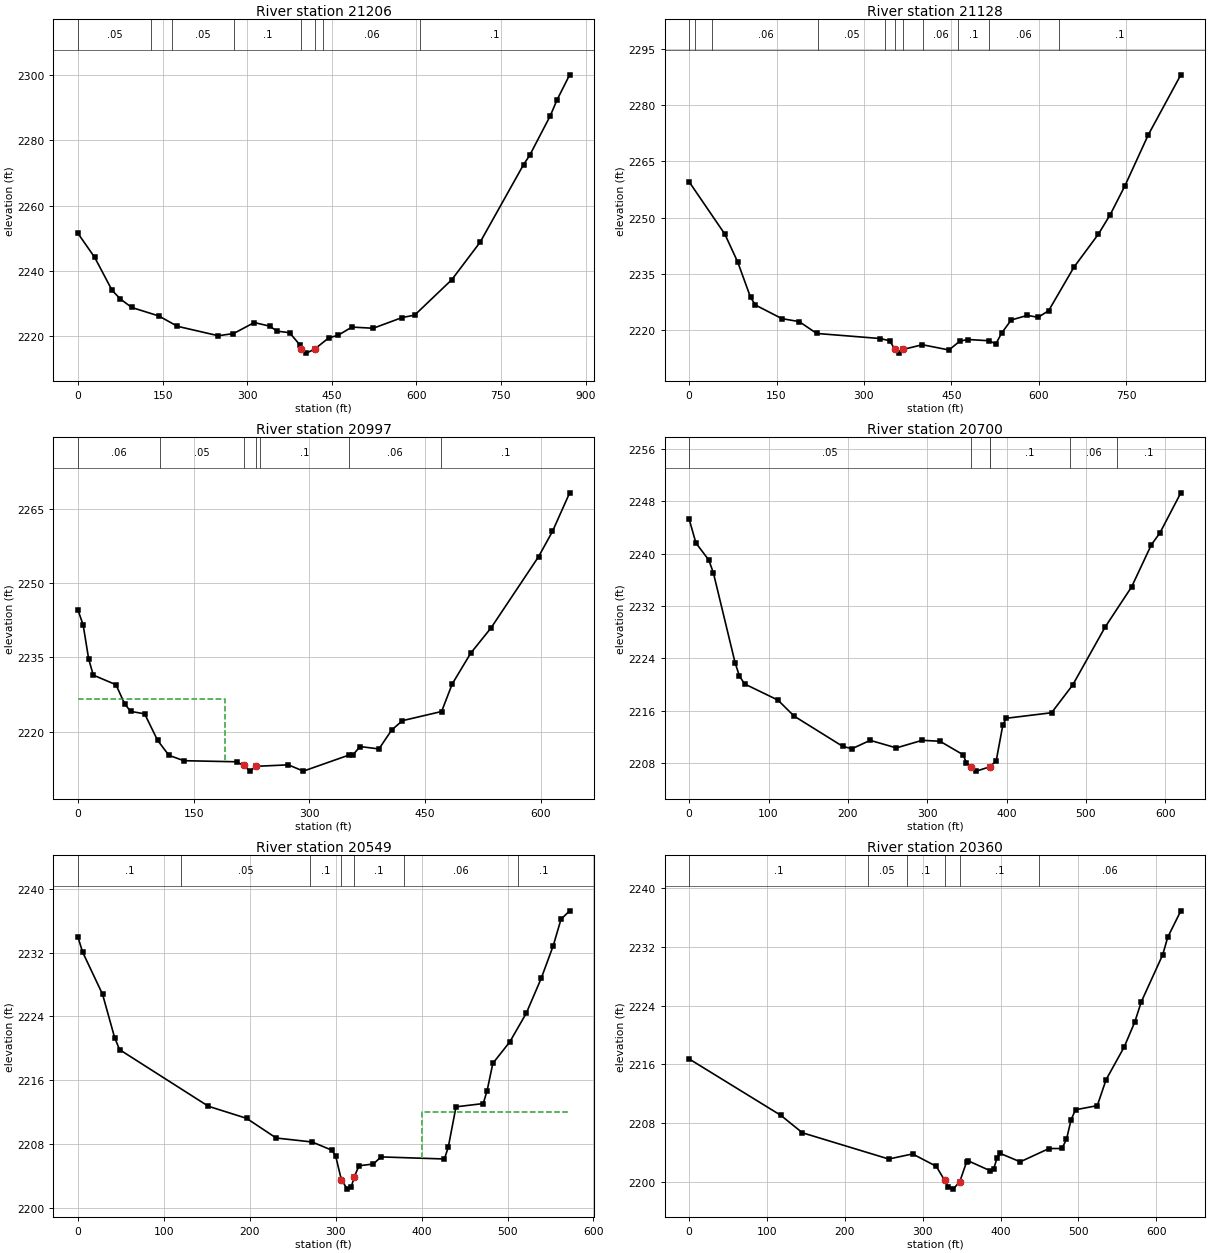
Type RM Length L Ch R = 1 ,21206   ,71.5,78.8,85.9
XS GIS Cut Line= 6
2217801.13341137655124.9169186292217953.69922251655192.509366603
2218080.19366086655264.9298465752218130.40519364655365.352912136
2218109.16185285 655484.12249929     2218332.074      655721.683
#Sta/Elev= 30
       0 2251.46    29.6 2244.13    60.4 2234.04    75.3 2231.37    95.2 2228.79
   143.3 2226.19   176.3 2223.02   248.7 2220.13   275.7 2220.79   312.6 2224.17
   339.7 2223.07   353.2 2221.53   375.2 2221.06   393.1 2217.39  396.25 2216.11
   405.2  2214.8   420.2  2216.1   444.7 2219.48   460.9 2220.24   485.8 2222.78
   523.5 2222.42     575 2225.71     597 2226.44   662.8 2237.29   713.2  2248.8
   790.2 2272.58   800.9 2275.36   837.7 2287.58   849.3 2292.31   871.9 2300.06
#Mann= 8 ,-1,0
       0     .05       0     130     .06       0  166.87     .05       0
  276.87      .1       0  396.25    .045       0   420.2      .1       0
   434.9     .06       0  606.17      .1       0
Bank Sta=396.25,420.2
XS Rating Curve= 0 ,0
Exp/Cntr=0.3,0.1

Type RM Length L Ch R = 1 ,21128   ,135.7,130.7,123.8
XS GIS Cut Line= 6
2217752.85309139655160.644355415 2217979.7705953655261.067420976
2218056.05350087655315.1413793552218059.91592647655383.699433729
2218036.74137288655463.8447648982218248.94066669655741.452688887
#Sta/Elev= 30
       0 2259.54    61.2 2245.61    83.3 2238.17   105.4 2228.72   113.7  2226.7
   159.1 2223.07   188.9 2222.27   218.8 2219.12     328 2217.76   344.1 2217.16
   352.6 2215.03   360.2 2213.87   366.9 2214.84   400.2 2216.11   445.9 2214.71
   464.7 2217.09   478.6  2217.5   514.9 2217.17   526.3 2216.31   536.3 2219.23
   552.7  2222.7   580.5 2223.94   598.8 2223.42   616.9 2225.18   660.4  2236.8
   702.4 2245.62   722.6 2250.79   747.8 2258.47     788  2272.1   843.8 2288.08
#Mann= 11 ,-1,0
       0      .1       0      10     .05       0      40     .06       0
  221.91     .05       0  335.71      .1       0   352.6    .045       0
   366.9      .1       0   402.1     .06       0  460.77      .1       0
  514.34     .06       0  634.34      .1       0
Bank Sta=352.6,366.9
XS Rating Curve= 0 ,0
Exp/Cntr=0.3,0.1

Type RM Length L Ch R = 1 ,20997   ,280.5,296.4,303.8
XS GIS Cut Line= 5
2217795.86675341655208.0689705172217860.62804342655265.087062809
2218024.64304964655472.7455470812218145.01457781655682.515812549
2218169.16857816655719.981555434
#Sta/Elev= 30
       0 2244.55     6.7 2241.54    13.8 2234.69    19.8 2231.41    49.2 2229.47
    60.5 2225.59    68.3 2224.07    86.4 2223.58   103.1 2218.24   117.8 2215.19
   137.2  2214.1   205.6 2213.88   214.6 2213.15   222.7 2211.99     2312212.964
   272.7 2213.26   292.1 2211.99   350.9 2215.22     356 2215.18   365.5 2216.96
   390.1 2216.48   406.7 2220.33   420.6  2222.2   471.3 2224.05   485.1 2229.63
   509.1 2235.86   535.5 2240.98     597 2255.37     615 2260.47   637.3 2268.28
#Mann= 7 ,-1,0
       0     .06       0  106.28     .05       0   214.6    .045       0
     231     .05       0  236.28      .1       0   350.9     .06       0
   470.9      .1       0
#XS Ineff= 2 , 0
          190.08 2226.51
Permanent Ineff=
       T       F
Bank Sta=214.6,231
XS Rating Curve= 0 ,0
Exp/Cntr=0.3,0.1

Type RM Length L Ch R = 1 ,20700   ,154,151.9,148.6
XS GIS Cut Line= 3
2217679.52667449655278.9816068672217884.62147377655497.112092543
2217973.26414126655804.754291465
#Sta/Elev= 30
       0 2245.27     8.5 2241.64    24.7 2239.04    30.5 2237.08    57.9 2223.31
    63.4 2221.27    69.9 2220.08   111.9 2217.61   132.2 2215.17   193.6 2210.53
   205.3 2210.18   228.1 2211.46   261.1  2210.3   293.5 2211.46   316.1 2211.32
   345.3 2209.25   349.4 2208.01   355.6 2207.37   361.9 2206.75   378.6  2207.4
   386.9 2208.31   395.2 2213.74   399.4 2214.83   456.7 2215.68   483.3 2219.92
   524.3  2228.8   557.6 2234.93   582.5 2241.38   593.2 2243.17   619.6 2249.31
#Mann= 6 ,-1,0
       0     .05       0   355.6    .045       0   378.6     .05       0
  379.41      .1       0  479.41     .06       0  539.41      .1       0
Bank Sta=355.6,378.6
XS Rating Curve= 0 ,0
Exp/Cntr(USF)=0,0
Exp/Cntr=0.3,0.1

Type RM Length L Ch R = 1 ,20549   ,198.8,188.4,178.9
XS GIS Cut Line= 4
2217587.92519826 655353.95478458 2217733.8390542655556.732128502
2217794.99412618655673.6777924572217884.04449414655842.122464392
#Sta/Elev= 30
       0 2233.93     5.4 2232.07    28.6 2226.78    42.6 2221.36    48.4 2219.84
   151.8 2212.74   196.2 2211.23   230.7 2208.76   272.6 2208.26   295.5 2207.23
     300 2206.47   306.52203.542   313.5 2202.35     318 2202.59   321.42203.847
   327.1 2205.28   343.8  2205.5   352.7 2206.39   426.5 2206.13     431 2207.61
     440 2212.67   471.7 2213.08   476.2  2214.7   482.9 2218.13   502.6 2220.81
   521.8 2224.41   539.2 2228.79   553.2 2232.88   562.2 2236.19   572.3 2237.25
#Mann= 7 ,-1,0
       0      .1       0     120     .05       0  269.82      .1       0
   306.5    .045       0   321.4      .1       0  379.82     .06       0
  511.79      .1       0
#XS Ineff= 2 , 0
                          400.23         2212.01
Permanent Ineff=
       F       F
Bank Sta=306.5,321.4
XS Rating Curve= 0 ,0
Exp/Cntr=0.3,0.1

Type RM Length L Ch R = 1 ,20360   ,169.5,171.5,171.3
XS GIS Cut Line= 4
2217511.51069337  655447.72183262217505.78628586 655666.88762594
2217672.13785778655737.296516446 2217836.7054415655900.414574594
#Sta/Elev= 30
       0 2216.74   117.8 2209.08   145.5 2206.71   256.4 2203.15     287 2203.84
   317.4 2202.16   328.32200.236   332.4 2199.41   339.1 2199.06   347.6 2200.07
   356.5 2202.79   358.5  2202.9   386.9 2201.55   391.2 2201.81   395.6 2203.32
   399.8  2203.9   425.3 2202.77   462.2 2204.57   478.8 2204.58   484.7 2205.82
   490.6 2208.48   496.3 2209.84   524.3  2210.4   535.6 2213.93   558.8 2218.36
   572.4 2221.75   580.8  2224.5   608.3 2230.89   614.8 2233.28   631.6 2236.86
#Mann= 6 ,-1,0
       0      .1       0  229.24     .05       0  279.24      .1       0
   328.3    .045       0   347.6      .1       0  449.88     .06       0
Bank Sta=328.3,347.6
XS Rating Curve= 0 ,0
Exp/Cntr=0.3,0.1

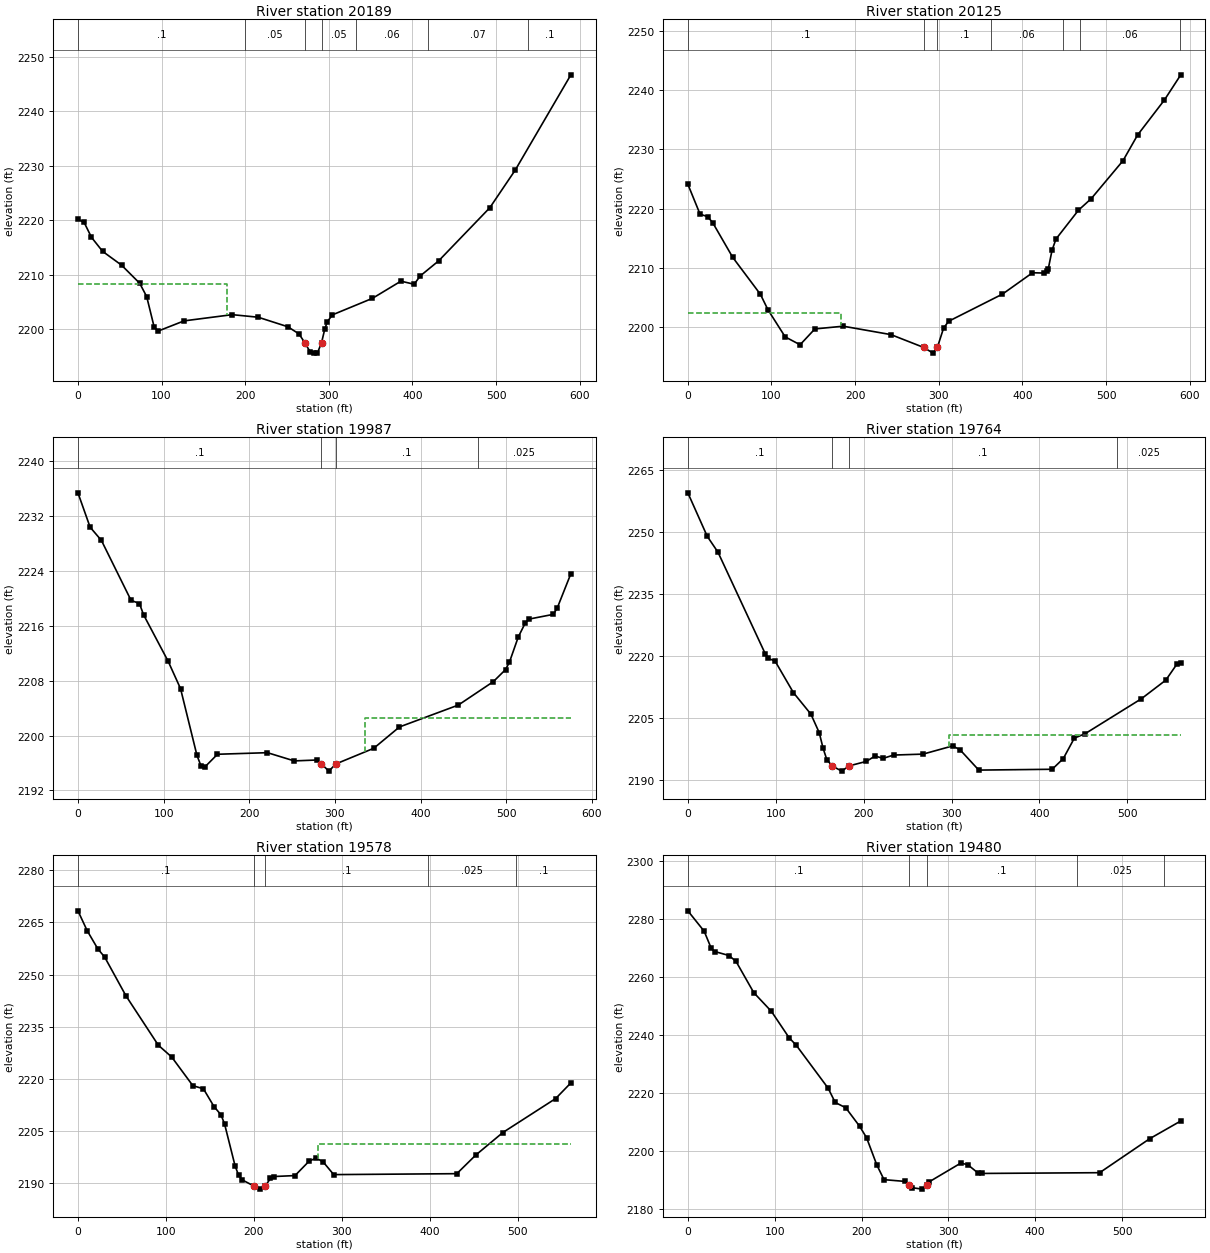
Type RM Length L Ch R = 1 ,20189   ,62.7,63.1,63
XS GIS Cut Line= 5
2217277.54270711655726.2655476932217469.09830901655817.290962427
2217578.01660458655869.3670508662217630.43525767655888.609341237
2217802.99597208655991.167992644
#Sta/Elev= 30
       0 2220.18     7.3 2219.64    16.2 2216.87    29.5  2214.3    52.2 2211.76
    73.8 2208.45    82.2    2206    91.2 2200.37    95.9 2199.67   126.9 2201.54
   184.5 2202.68   215.5 2202.21     251 2200.46   264.3 2199.15   271.3 2197.52
   277.6 2195.87     282 2195.62   286.4 2195.67  291.25 2197.52   295.3 2200.13
   298.3  2201.4   304.2 2202.64   352.2 2205.68   386.2 2208.83     402 2208.26
   409.3 2209.79   431.2 2212.54   492.5 2222.31   522.9 2229.22   589.4  2246.7
#Mann= 7 ,-1,0
       0      .1       0     200     .05       0   271.3    .045       0
  291.25     .05       0  332.08     .06       0  418.65     .07       0
  538.65      .1       0
#XS Ineff= 2 , 0
          177.86  2208.3
Permanent Ineff=
       F       F
Bank Sta=271.3,291.25
XS Rating Curve= 0 ,0
Exp/Cntr=0.3,0.1

Type RM Length L Ch R = 1 ,20125   ,136.5,138.9,140.5
XS GIS Cut Line= 5
2217235.00317434 655774.736881882217426.55877625655865.762296614
2217535.47707182655917.838385053 2217587.8957249655937.080675424
2217760.45643931 656039.63932683
#Sta/Elev= 30
       0 2224.11    14.6 2219.06    23.7 2218.64    29.7 2217.63    53.7 2211.77
    86.8 2205.54    95.8 2202.94   116.4 2198.37   134.2 2197.04   151.9 2199.71
   185.8 2200.17   242.9 2198.75   281.8  2196.6   293.2 2195.63  298.38  2196.6
   305.8 2199.85   311.8    2201   376.2 2205.58   412.1 2209.18   426.2 2209.13
   429.8 2209.56   430.9 2209.79   435.5 2212.98   440.2 2214.87   467.1 2219.73
   482.3 2221.67   520.3 2228.07   537.8 2232.41   569.9 2238.32   589.4 2242.55
#Mann= 7 ,-1,0
       0      .1       0   281.8    .045       0  298.38      .1       0
  362.81     .06       0  448.65      .1       0  468.65     .06       0
  588.65      .1       0
#XS Ineff= 2 , 0
          183.57 2202.38
Permanent Ineff=
       F       F
Bank Sta=281.8,298.38
XS Rating Curve= 0 ,0
Exp/Cntr=0.3,0.1

Type RM Length L Ch R = 1 ,19987   ,221.5,222.2,212
XS GIS Cut Line= 3
2217168.34855545655843.0306777562217457.38882989656034.507529984
2217653.71324135656151.843055039
#Sta/Elev= 30
       0  2235.4    14.2 2230.39    27.4 2228.46      62 2219.72    71.8 2219.26
    76.6 2217.62   105.3 2210.84   119.8 2206.84   138.9 2197.13   143.7 2195.56
   148.5 2195.47   162.9 2197.28   221.2 2197.51   252.5 2196.31   278.5 2196.44
   284.3 2195.87   292.9 2194.82     3012195.863   345.3 2198.15   375.3 2201.26
     444 2204.45   484.9 2207.87   499.1 2209.62   503.7 2210.71     514 2214.38
   522.4 2216.48     527    2217     555 2217.68   559.7 2218.67   575.4 2223.61
#Mann= 4 ,-1,0
       0      .1       0   284.3    .045       0     301      .1       0
  466.71    .025       0
#XS Ineff= 2 , 0
                          335.16         2202.63
Permanent Ineff=
       F       F
Bank Sta=284.3,301
XS Rating Curve= 0 ,0
Exp/Cntr=0.3,0.1

Type RM Length L Ch R = 1 ,19764   ,189.9,186.6,180.5
XS GIS Cut Line= 5
2217090.39237074656041.2072452572217193.25029378656059.006517887
2217311.84792574656098.9191824912217519.95395523656164.953191208
2217628.52481725656196.090511757
#Sta/Elev= 30
       0 2259.42    22.1 2248.88    34.3 2245.04      88 2220.48    91.1 2219.35
    99.2  2218.7   120.1 2211.04     140 2205.83   149.5 2201.33   153.9 2197.55
   158.1 2194.83  164.15  2193.3     175 2192.03   183.4 2193.29   203.1 2194.39
     213 2195.69   222.1 2195.12   234.1 2195.92   267.6 2196.15   301.2 2198.13
   309.6 2197.22     331 2192.28   414.5 2192.48   427.1 2195.05   439.7 2200.01
   452.2 2201.12   516.1 2209.57   543.8 2214.07   556.3 2217.91   560.8 2218.17
#Mann= 4 ,-1,0
       0      .1       0  164.15    .045       0   183.4      .1       0
  487.85    .025       0
#XS Ineff= 2 , 0
                          296.79         2200.82
Permanent Ineff=
       F       T
Bank Sta=164.15,183.4
XS Rating Curve= 0 ,0
Exp/Cntr=0.3,0.1

Type RM Length L Ch R = 1 ,19578   ,99.5,98.1,96.9
XS GIS Cut Line= 3
2217061.64657829 656253.317564122217329.71137242656262.490745193
2217621.45003394656275.005004132
#Sta/Elev= 30
       0 2268.36    10.5 2262.64    22.5 2257.45    30.5 2254.99    54.6 2243.87
    91.3 2229.68   106.6 2226.25   130.6 2218.01   142.6 2217.12   154.6 2212.01
   162.6 2209.61   166.6 2207.02   178.6 2194.91   182.6 2192.21   186.6 2190.89
   199.7 2189.15   206.6 2188.22  213.02 2189.14   218.7 2191.29   222.7 2191.85
   246.7 2192.12   262.7 2196.27   270.7 2197.16   278.7 2196.05   290.7  2192.4
   430.6 2192.67     452    2198   482.9 2204.52   542.9  2214.3   560.2 2218.81
#Mann= 5 ,-1,0
       0      .1       0   199.7    .045       0  213.02      .1       0
  398.22    .025       0  498.22      .1       0
#XS Ineff= 2 , 0
                          272.45         2201.23
Permanent Ineff=
       F       T
Bank Sta=199.7,213.02
XS Rating Curve= 0 ,0
Exp/Cntr=0.3,0.1

Type RM Length L Ch R = 1 ,19480   ,76.4,78.3,79.2
XS GIS Cut Line= 4
2217017.70921841656331.8338763092217186.98836501656365.212862963
2217312.15956496656354.4839029672217581.57567153656355.676009634
#Sta/Elev= 30
       0 2282.86    18.8 2275.83      27 2269.88    31.1 2268.81    47.4 2267.44
    55.5 2265.41    75.9 2254.65    96.3 2248.15   116.7 2239.04   124.8 2236.51
   161.5  2221.7   169.7 2216.75   181.8 2214.94   197.8 2208.54   205.8  2204.6
   217.7 2195.13   225.9 2190.13     250 2189.52     255 2188.22     258 2187.37
   269.8 2186.86  274.84 2188.24   278.1 2189.41   314.2 2195.82   322.2 2195.32
   334.2  2192.4   338.2 2192.27   474.2 2192.53   531.8 2204.25   567.6 2210.37
#Mann= 5 ,-1,0
       0      .1       0     255    .045       0  274.84      .1       0
  448.17    .025       0  548.17      .1       0
Bank Sta=255,274.84
XS Rating Curve= 0 ,0
Exp/Cntr(USF)=0,0
Exp/Cntr=0.3,0.1

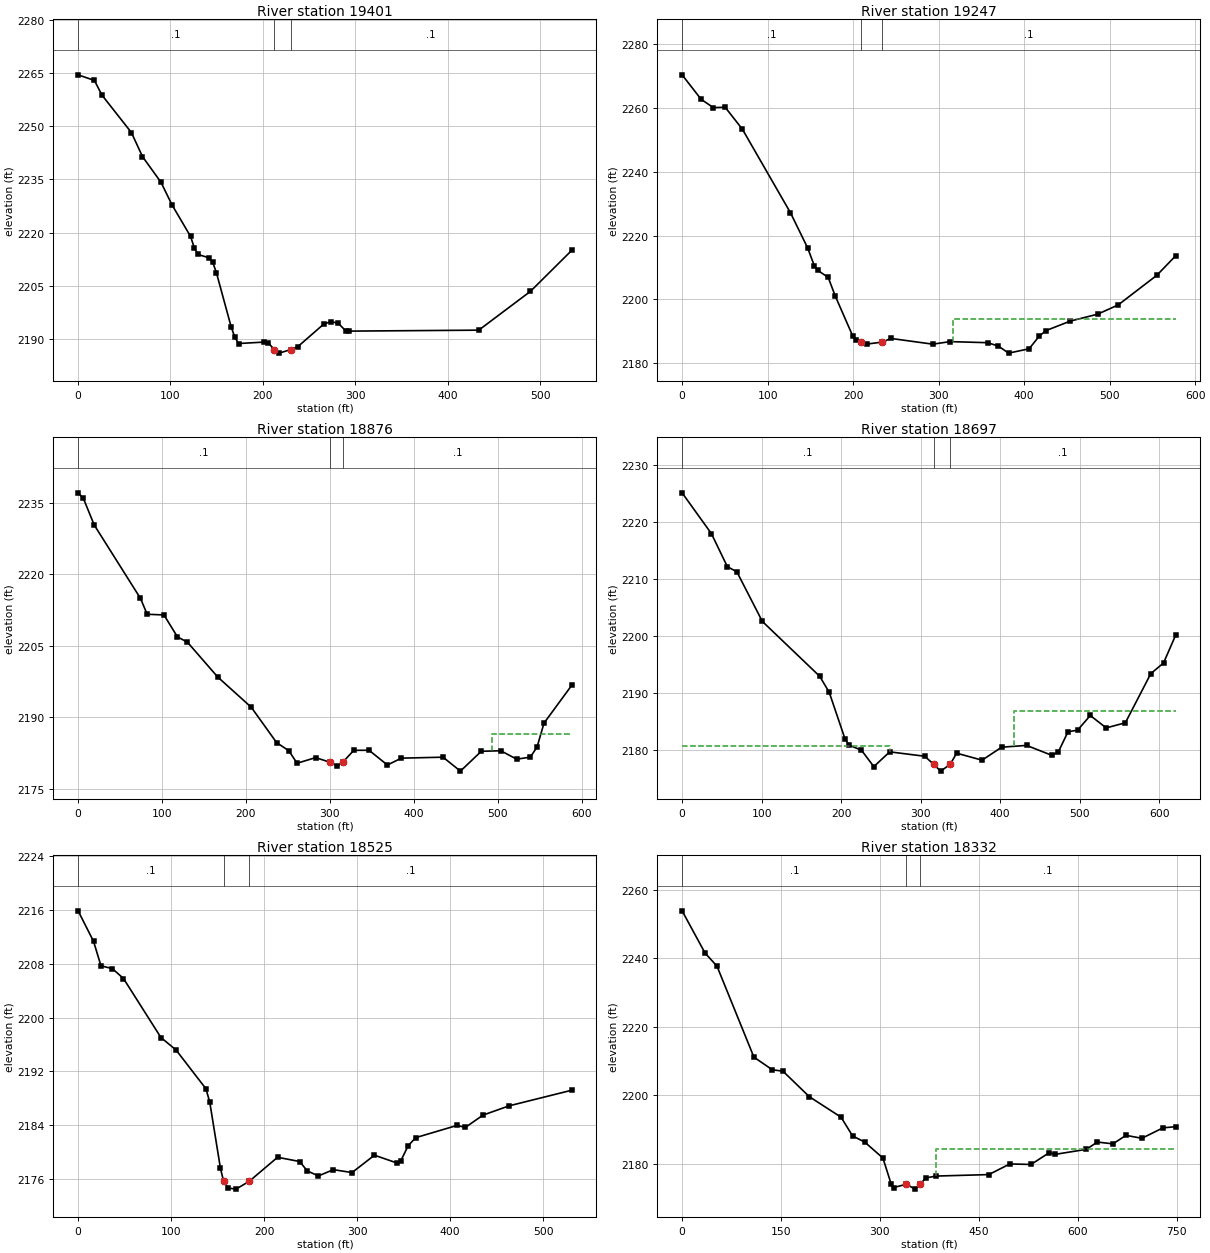
Type RM Length L Ch R = 1 ,19401   ,151.6,154.6,156.6
XS GIS Cut Line= 2
 2217062.4937132 656432.485322692217596.91340311656436.674123251
#Sta/Elev= 30
       0 2264.52    17.7 2262.93    25.7 2258.84    57.7 2248.24    69.7 2241.45
    89.7 2234.22   101.7 2227.81   121.7 2218.95   125.7  2215.8   129.7 2213.85
   141.7  2212.9   145.7 2211.64   149.7 2208.71   165.7  2193.4   169.7 2190.46
   173.7 2188.72   201.7 2189.13   205.7 2188.95  212.32 2187.03   217.7 2186.01
   230.12187.008   237.7  2187.8   265.7 2194.16   273.7 2194.93   281.7  2194.4
   289.7 2192.31   293.7 2192.22   433.7 2192.49   489.7 2203.45   534.4 2215.01
#Mann= 3 ,-1,0
       0      .1       0  212.32    .045       0   230.1      .1       0
Bank Sta=212.32,230.1
XS Rating Curve= 0 ,0
Exp/Cntr=0.3,0.1

Type RM Length L Ch R = 1 ,19247   ,381.4,370.7,356.8
XS GIS Cut Line= 4
2217038.01285885656559.5754280532217212.81124557656575.896107419
2217366.63234503656606.3127090082217611.55365954656599.262176326
#Sta/Elev= 30
       0 2270.42    22.3 2262.74    36.5 2260.15    50.4 2260.25    70.5 2253.38
   126.7 2227.21   146.8 2216.19   154.8 2210.47   158.8  2209.1   170.9 2206.91
     179 2201.17   199.4 2188.66   203.3 2187.28   208.7 2186.62   215.7    2186
   234.1 2186.64   244.3 2187.78   293.2 2185.99   313.5 2186.79   357.5 2186.45
     370 2185.37   381.9 2183.18   405.9 2184.54   417.9 2188.58   425.9 2190.27
     454 2193.22     486 2195.39     510 2198.28   555.3 2207.59   577.4 2213.73
#Mann= 3 ,-1,0
       0      .1       0   208.7    .045       0   234.1      .1       0
#XS Ineff= 2 , 0
                          317.06         2193.86
Permanent Ineff=
       F       F
Bank Sta=208.7,234.1
XS Rating Curve= 0 ,0
Exp/Cntr=0.3,0.1

Type RM Length L Ch R = 1 ,18876   ,168.6,179.3,184.8
XS GIS Cut Line= 4
2217037.88737638656940.1824016942217262.08547978656940.888758383
2217358.87811817656873.3093304872217596.10153919656808.548040477
#Sta/Elev= 30
       0 2237.08     6.3 2235.91    19.2 2230.34    74.3 2214.96    82.3 2211.63
   102.3 2211.49   118.3 2206.91   130.3 2205.77   166.3 2198.49   206.3 2192.15
   236.5 2184.74   251.1 2183.03   260.9 2180.41   282.9 2181.59   299.9 2180.64
   308.8  2179.8  315.37 2180.64   328.5 2183.12   346.7 2183.13   368.5 2180.04
   385.1 2181.48   434.8 2181.68   455.5 2178.76   480.4 2182.92   503.6 2183.03
   522.6 2181.26   538.8  2181.7   546.8  2183.8   555.1 2188.82   588.2 2196.76
#Mann= 3 ,-1,0
       0      .1       0   299.9    .045       0  315.37      .1       0
#XS Ineff= 2 , 0
                          493.19          2186.5
Permanent Ineff=
       F       F
Bank Sta=299.9,315.37
XS Rating Curve= 0 ,0
Exp/Cntr=0.3,0.1

Type RM Length L Ch R = 1 ,18697   ,175.5,171.2,175.6
XS GIS Cut Line= 3
2217083.43962913657029.1544985852217147.81338911657024.862914587
2217703.57351689657000.186306596
#Sta/Elev= 30
       0 2225.18    36.8 2218.04    56.9 2212.24    68.9 2211.32   100.9 2202.63
     173 2193.01     185  2190.2     205 2181.97   210.2 2180.92   225.6 2180.03
   241.1 2177.16   261.1 2179.75   305.1 2178.98   316.6 2177.54   325.1 2176.37
   337.1 2177.54   345.2 2179.52   377.2 2178.29   401.9 2180.57   433.2 2180.88
   465.3 2179.12   473.3 2179.79   485.3 2183.28   497.3 2183.55   513.3 2186.13
   533.3 2183.95   557.4 2184.85   589.4 2193.47   605.4 2195.34   620.8 2200.26
#Mann= 3 ,-1,0
       0      .1       0   316.6    .045       0   337.1      .1       0
#XS Ineff= 2 , 0
           260.9 2180.86  417.24         2186.96
Permanent Ineff=
       F       F
Bank Sta=316.6,337.1
XS Rating Curve= 0 ,0
Exp/Cntr=0.3,0.1

Type RM Length L Ch R = 1 ,18525   ,194.8,193.9,191.4
XS GIS Cut Line= 3
2217119.74642976657102.3152767972217343.96023575657130.993786866
2217647.25720588657162.279434214
#Sta/Elev= 30
       0 2215.85    16.6 2211.32    24.6 2207.68    36.7 2207.28    48.8  2205.8
    89.1 2197.03   105.3 2195.19   137.5 2189.42   141.6 2187.42   153.1 2177.59
  156.54 2175.66   161.7 2174.68   169.8 2174.52   184.1 2175.69   214.5 2179.25
   238.3 2178.62   246.4 2177.23   258.4 2176.48   274.5 2177.41   294.6 2176.98
   318.7 2179.56   342.9  2178.4   346.9 2178.69   354.9 2180.95     363 2182.16
   407.2 2183.97   416.6  2183.7   435.4 2185.51   463.5 2186.89   530.9 2189.21
#Mann= 3 ,-1,0
       0      .1       0  156.54    .045       0   184.1      .1       0
Bank Sta=156.54,184.1
XS Rating Curve= 0 ,0
Exp/Cntr=0.3,0.1

Type RM Length L Ch R = 1 ,18332   ,239.9,249.3,257.6
XS GIS Cut Line= 4
2216975.29171237657299.3097112822217120.13267232657298.236815283
     2217329.712       657306.65  2217723.626936657316.861160016
#Sta/Elev= 30
       0  2253.8    34.8  2241.5    52.9 2237.67   108.9 2211.14   136.9 2207.44
   152.9 2207.05   192.9 2199.61     241 2193.63   258.6 2188.15     277 2186.36
   304.5 2181.72     317 2174.16     321 2173.12   340.2 2174.08   353.1 2172.65
  361.33 2174.06   369.1  2175.9   385.1 2176.46   465.1 2176.89   497.1    2180
   529.1 2179.84   557.1 2183.32   565.1 2182.77     613 2184.25   629.7 2186.38
   653.2 2185.85   673.2 2188.33   697.2 2187.47   729.2 2190.52   748.6 2190.86
#Mann= 3 ,-1,0
       0      .1       0   340.2    .045       0  361.33      .1       0
#XS Ineff= 2 , 0
                          385.37         2184.23
Permanent Ineff=
       F       F
Bank Sta=340.2,361.33
XS Rating Curve= 0 ,0
Exp/Cntr=0.3,0.1

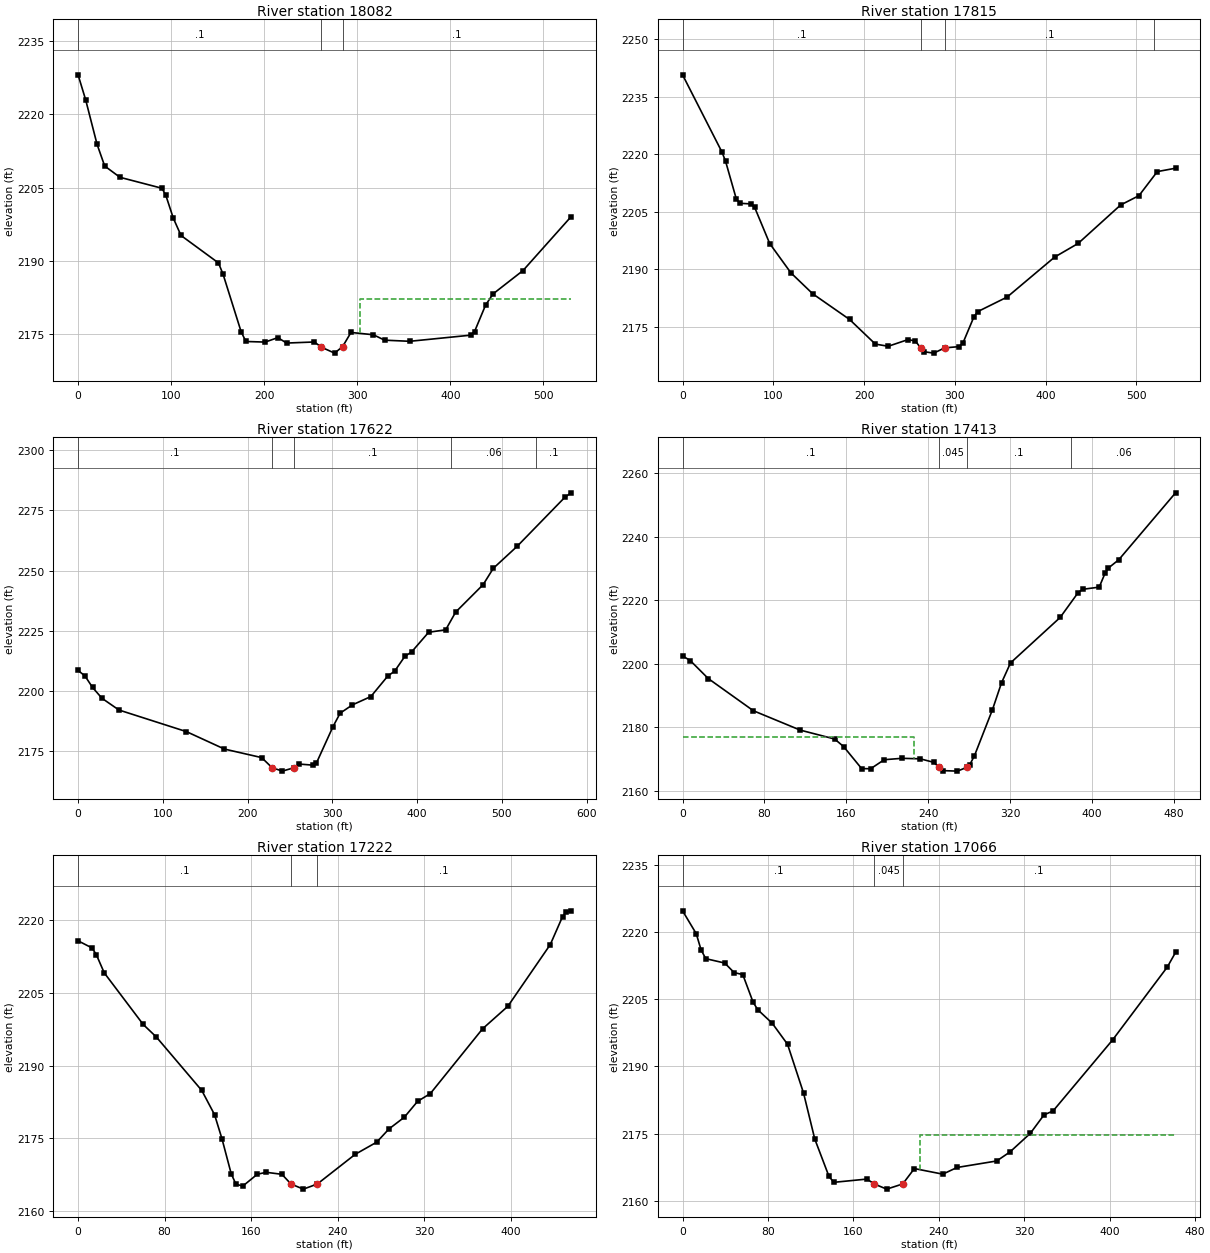
Type RM Length L Ch R = 1 ,18082   ,277.5,267,253.4
XS GIS Cut Line= 4
2217044.21265775 657427.10721543 2217171.4942799657455.349164117
2217321.83919632657562.241792556 2217535.6244532657583.098890788
#Sta/Elev= 30
       0 2228.08     8.2 2222.94    20.4 2213.87    28.6 2209.43      45 2207.12
    90.1 2204.88    94.2 2203.48   102.3 2198.77   110.6 2195.22   150.8 2189.61
   155.8 2187.28   175.2 2175.52   180.3 2173.54     201 2173.42   214.6 2174.33
     224 2173.22   253.9 2173.44   261.3 2172.38   275.6 2171.16   284.2  2172.5
   293.2 2175.39   317.2 2174.92   329.3 2173.81   356.3 2173.58   421.7 2174.83
   425.9 2175.56   437.8 2180.99   445.8 2183.27     478 2188.05   529.6 2199.06
#Mann= 3 ,-1,0
       0      .1       0   261.3    .045       0   284.2      .1       0
#XS Ineff= 2 , 0
                          303.21         2182.29
Permanent Ineff=
       F       F
Bank Sta=261.3,284.2
XS Rating Curve= 0 ,0
Exp/Cntr=0.3,0.1

Type RM Length L Ch R = 1 ,17815   ,187.7,192.9,195.7
XS GIS Cut Line= 4
2216984.96130395657779.6753680342217129.51305154657786.896678017
  2217371.691905657752.977667044 2217524.1623476657732.473432385
#Sta/Elev= 30
       0 2240.72    43.3 2220.64    47.3 2218.26    59.3 2208.29    63.3 2207.24
    75.3 2207.08    79.3 2206.24      96 2196.75   119.4  2189.1   143.4 2183.65
     184 2176.96   212.4 2170.54   226.6 2169.98   248.4 2171.72   256.5 2171.35
  262.31 2169.54   265.5 2168.57   276.7 2168.19   288.8 2169.56   304.9 2169.89
     309  2170.9   321.1 2177.72   325.1    2179   357.6 2182.81   409.9 2193.22
   435.8 2196.78   482.6  2206.8   502.8 2209.23     523  2215.5   543.1 2216.38
#Mann= 4 ,-1,0
       0      .1       0  262.31    .045       0   288.8      .1       0
  519.27     .06       0
Bank Sta=262.31,288.8
XS Rating Curve= 0 ,0
Exp/Cntr=0.3,0.1

Type RM Length L Ch R = 1 ,17622   ,202.3,209.5,215.7
XS GIS Cut Line= 2
2217020.12147655657930.7013375322217599.52944824657981.172415205
#Sta/Elev= 30
       0 2208.56     8.1 2206.32    17.1 2201.52    28.2 2197.03    48.2 2192.17
   127.9 2183.19   172.7 2175.96   216.6 2172.42   228.9 2168.24     241 2166.81
  254.51 2168.19     261 2169.74   277.1 2169.29   281.1 2170.08   300.8 2185.31
   309.2 2190.85   323.7  2194.3   345.4 2197.74   365.4 2206.25   373.5 2208.29
   385.5  2214.4   393.5 2216.26   413.6 2224.42   433.7 2225.43   445.5 2232.79
   477.9 2244.18   489.9 2250.95     518 2260.07   574.2 2280.37   581.6 2282.26
#Mann= 5 ,-1,0
       0      .1       0   228.9    .045       0  254.51      .1       0
     440     .06       0     540      .1       0
Bank Sta=228.9,254.51
XS Rating Curve= 0 ,0
Exp/Cntr=0.3,0.1

Type RM Length L Ch R = 1 ,17413   ,185.9,191.4,197.3
XS GIS Cut Line= 2
2217017.38318782658031.2862795872217454.54062339 658233.88480751
#Sta/Elev= 30
       0 2202.44     7.5 2200.98    25.1 2195.31    69.2 2185.16     115 2179.05
   148.6 2176.25   157.4 2173.86     175 2166.92   183.8 2166.87   197.1 2169.72
   214.4 2170.16   232.3    2170   245.6 2168.88   250.6 2167.35   254.4 2166.28
   268.6 2166.12   277.7  2167.3   280.7 2168.17   285.2 2170.92   302.9 2185.53
   311.7 2193.95   320.5 2200.23     369 2214.56   386.6  2222.4     391 2223.44
   407.2 2224.13   413.1 2228.66   416.2 2230.16   426.3 2232.76   481.8 2253.86
#Mann= 4 ,-1,0
       0      .1       0   250.6    .045       0   277.7      .1       0
     380     .06       0
#XS Ineff= 2 , 0
          225.71 2177.03
Permanent Ineff=
       F       F
Bank Sta=250.6,277.7
XS Rating Curve= 0 ,0
Exp/Cntr=0.3,0.1

Type RM Length L Ch R = 1 ,17222   ,160.1,155.9,149.9
XS GIS Cut Line= 3
2216971.73742357658131.3636342162217195.85347682658336.405980804
 2217319.8325701658424.621874104
#Sta/Elev= 30
       0 2215.76    12.9 2214.29    16.9  2212.9    24.2 2209.15    60.2  2198.5
    72.4  2195.9   114.4 2184.87   126.2 2179.88   133.1 2174.88   141.6 2167.69
     146 2165.51   152.4 2165.14   165.8 2167.58   174.1 2167.97   188.5 2167.56
   196.9 2165.56   208.3  2164.5  221.21 2165.55   256.4  2171.7   276.2  2174.2
   287.5 2176.92   301.7 2179.34     314 2182.62   325.8 2184.23   374.1  2197.6
   397.4 2202.23   436.7 2214.99     448 2220.74   451.4 2221.71   455.9 2221.95
#Mann= 3 ,-1,0
       0      .1       0   196.9    .045       0  221.21      .1       0
Bank Sta=196.9,221.21
XS Rating Curve= 0 ,0
Exp/Cntr=0.3,0.1

Type RM Length L Ch R = 1 ,17066   ,240.5,234,220.1
XS GIS Cut Line= 3
2216860.62893961658309.4679495572217096.66605952658423.194925514
2217283.34996345658494.006061487
#Sta/Elev= 30
       0 2224.82    12.8 2219.71    17.3 2216.11    21.7 2214.12    39.5 2213.14
    48.3    2211    56.4 2210.56    66.1 2204.35    70.5 2202.68    83.9 2199.69
    98.3 2194.97   113.3 2184.06   123.8 2173.78   137.1 2165.42   141.6 2164.08
   172.7 2164.81  179.53 2163.71   191.2 2162.56   206.2 2163.72   217.1 2167.16
   243.7 2165.91     257  2167.4   294.2 2168.86   306.6 2170.87   325.7 2175.04
   338.5 2179.17     347 2180.05   402.7 2195.93     454 2212.25   461.7 2215.52
#Mann= 3 ,-1,0
       0      .1       0  179.53    .045       0   206.2      .1       0
#XS Ineff= 2 , 0
                          222.82         2174.69
Permanent Ineff=
       F       F
Bank Sta=179.53,206.2
XS Rating Curve= 0 ,0
Exp/Cntr=0.3,0.1