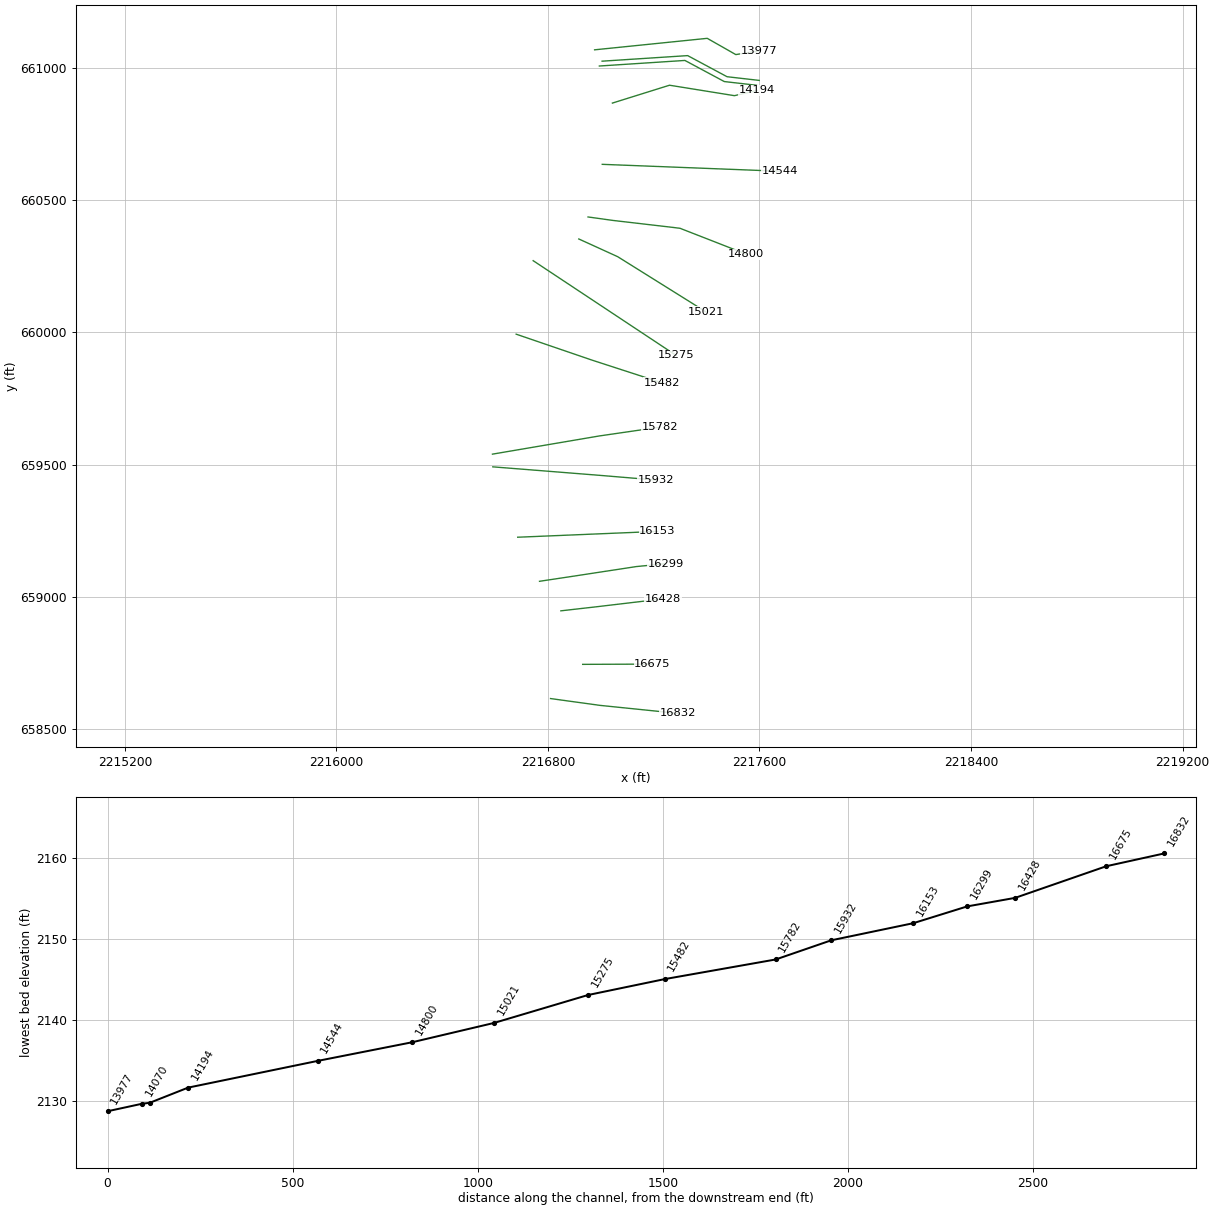
HEC-RAS study JENKSFK.prj: JENKSFK

--- JENKSFK.g01 (geometry) --- (continued)

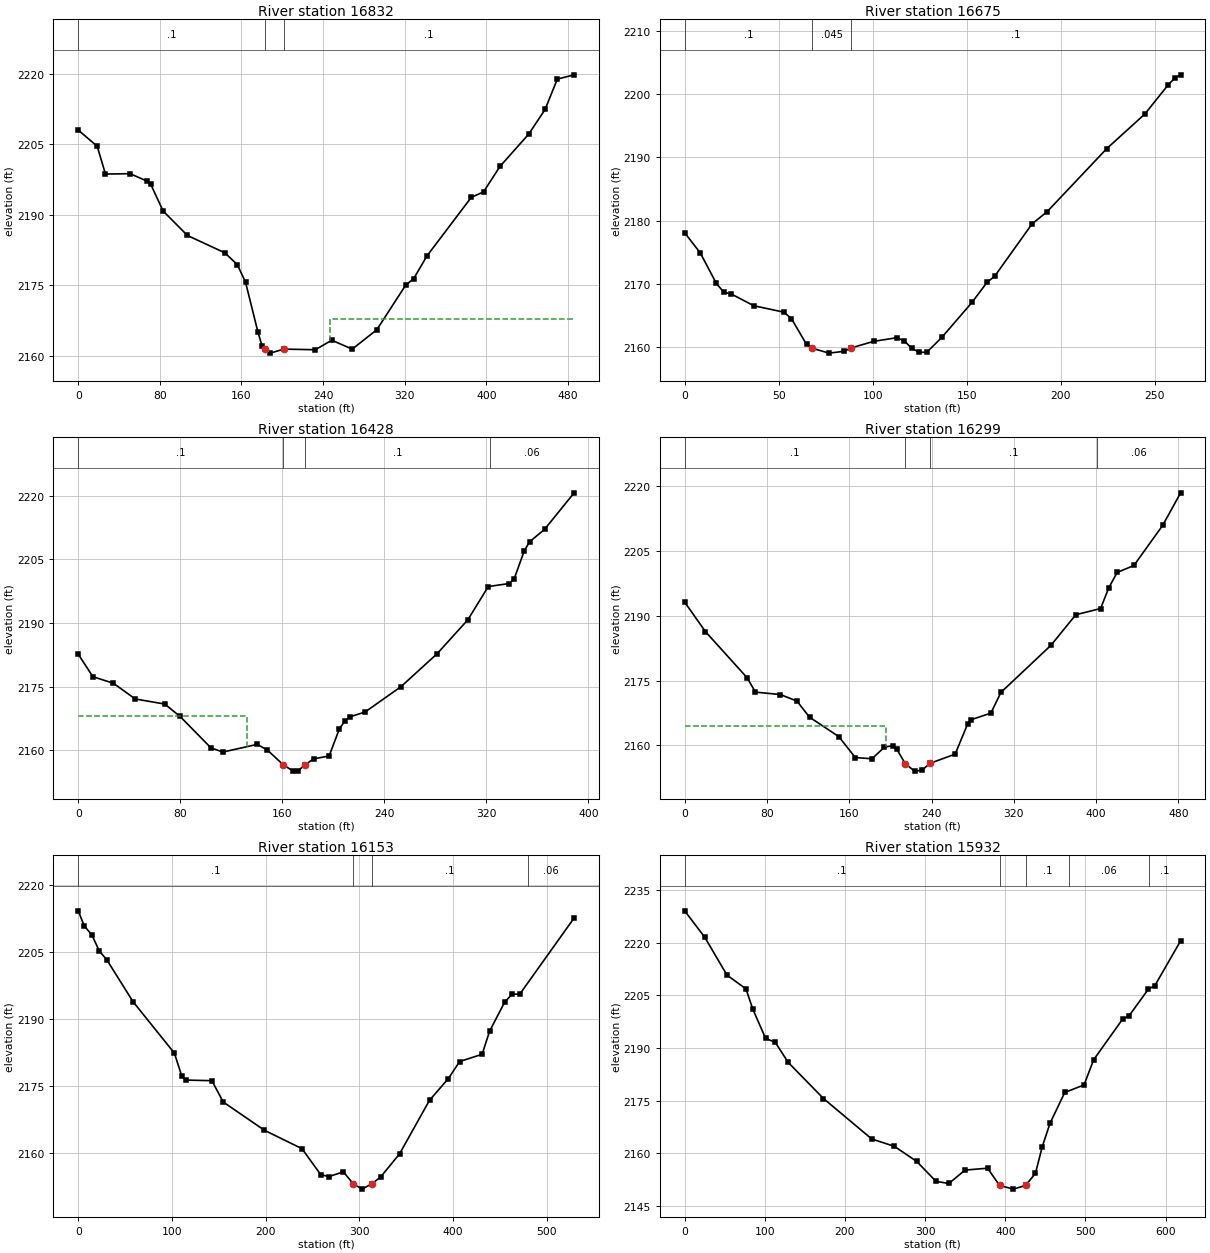
Type RM Length L Ch R = 1 ,16832   ,154.9,156.9,158.2
XS GIS Cut Line= 3
2216809.75247622658615.309537589      2216997.07       658589.52
2217292.55567604658559.280524277
#Sta/Elev= 30
       0 2208.07    18.6 2204.63    26.7  2198.7    50.9 2198.78      67 2197.24
    71.1 2196.52    83.2 2190.84     107 2185.63   143.8 2181.92   155.9 2179.42
     164 2175.69   176.1  2165.1   180.1 2162.18     183 2161.43   188.2 2160.57
  201.67 2161.43   232.4 2161.29   248.5 2163.32   268.6 2161.42   292.7 2165.56
   320.9 2175.02   328.9 2176.46   341.8 2181.26   385.2 2193.72   397.3 2194.91
   413.4 2200.33   441.5 2207.19   457.6 2212.45   469.6 2218.92   486.1 2219.83
#Mann= 3 ,-1,0
       0      .1       0     183    .045       0  201.67      .1       0
#XS Ineff= 2 , 0
                          247.23         2167.93
Permanent Ineff=
       F       F
Bank Sta=183,201.67
XS Rating Curve= 0 ,0
Exp/Cntr=0.3,0.1

Type RM Length L Ch R = 1 ,16675   ,243.4,246.4,246.2
XS GIS Cut Line= 3
2216931.36728906658744.6619835122217106.10020596658745.284718286
2217195.15778146658745.613827837
#Sta/Elev= 30
       0 2178.07     8.3 2174.87    16.8 2170.06    20.8 2168.64    24.8 2168.36
    36.8  2166.5    52.8 2165.48    56.8 2164.46    64.8 2160.37   67.64 2159.78
    76.8 2158.99    84.8 2159.28    88.6 2159.82   100.6 2160.86   112.8 2161.43
   116.8 2160.93   120.8 2159.75   124.8 2159.12   128.8 2159.13   136.8 2161.49
   152.8 2167.02   160.8 2170.19   164.9 2171.18   184.8 2179.48   192.8 2181.41
   224.5  2191.4   244.8  2196.9   257.2 2201.51   260.8 2202.64   263.8  2203.1
#Mann= 3 ,-1,0
       0      .1       0   67.64    .045       0    88.6      .1       0
Bank Sta=67.64,88.6
XS Rating Curve= 0 ,0
Exp/Cntr=0.3,0.1

Type RM Length L Ch R = 1 ,16428   ,128.7,129.3,129.4
XS GIS Cut Line= 3
2216848.79491899658947.0711994092216980.51281288658962.055773063
2217235.00490733658992.177868709
#Sta/Elev= 30
       0 2182.64    11.5 2177.33    27.6 2175.78    44.7 2172.08    67.8 2170.89
    79.9 2167.96     104 2160.58   113.4 2159.58   140.3 2161.39   148.3 2160.06
   160.6 2156.62   168.5 2155.09   172.5 2155.21     178 2156.61   184.6 2157.98
   196.7 2158.66   204.7 2165.01   208.8  2166.8   212.8 2167.86   224.9 2169.01
   253.1    2175   281.3 2182.72   305.4 2190.71   321.5 2198.56   337.7 2199.26
   341.7 2200.31   349.7 2206.98   353.8 2209.08   365.6 2212.03   388.8 2220.63
#Mann= 4 ,-1,0
       0      .1       0   160.6    .045       0     178      .1       0
  322.57     .06       0
#XS Ineff= 2 , 0
          132.51 2168.19
Permanent Ineff=
       F       F
Bank Sta=160.6,178
XS Rating Curve= 0 ,0
Exp/Cntr=0.3,0.1

Type RM Length L Ch R = 1 ,16299   ,147.8,145.8,144
XS GIS Cut Line= 4
2216768.15530463659058.7680415552216889.39255258659077.007273548
2217135.08573649659114.5586335342217245.59402445 659125.28759353
#Sta/Elev= 30
       0 2193.15    20.2 2186.32    60.7 2175.65    68.8 2172.32    93.1 2171.76
   109.2 2170.24   121.4 2166.52   149.8 2162.04   165.9 2157.19   182.1  2156.9
   194.2 2159.59   202.3 2159.92   206.3 2159.11   214.4 2155.78   223.5 2154.04
   230.5 2154.22   238.7 2155.86     263 2157.98   275.1 2164.95   278.6 2165.95
   297.7 2167.46   307.5 2172.26   356.1 2183.15   380.3 2190.23   404.4 2191.66
   412.4  2196.5   420.5 2200.01   436.8 2201.63   464.7 2210.89   482.2 2218.44
#Mann= 4 ,-1,0
       0      .1       0   214.4    .045       0   238.7      .1       0
  401.15     .06       0
#XS Ineff= 2 , 0
          196.06 2164.42
Permanent Ineff=
       F       F
Bank Sta=214.4,238.7
XS Rating Curve= 0 ,0
Exp/Cntr=0.3,0.1

Type RM Length L Ch R = 1 ,16153   ,223.9,221.6,219.5
XS GIS Cut Line= 2
2216685.65522219659225.4252148532217214.32803435659247.454443399
#Sta/Elev= 30
       0  2214.3     6.5 2210.89    14.5 2208.95    22.5  2205.3    30.5 2203.33
    58.6 2193.92   102.6 2182.43   110.6 2177.23   114.6 2176.39   142.6 2176.26
   154.7 2171.48   198.7 2165.15   238.7 2161.03   258.7 2155.23   267.4 2154.77
   282.8 2155.84  293.46 2153.18   302.8 2151.97   313.5 2153.19   322.8 2154.73
   342.8 2159.86   374.8 2171.87   394.9 2176.73   406.9 2180.54   430.9 2182.17
   438.9 2187.35   454.9 2193.83   462.9 2195.64   471.1 2195.64   529.1 2212.71
#Mann= 4 ,-1,0
       0      .1       0  293.46    .045       0   313.5      .1       0
     480     .06       0
Bank Sta=293.46,313.5
XS Rating Curve= 0 ,0
Exp/Cntr=0.3,0.1

Type RM Length L Ch R = 1 ,15932   ,144.8,150,154.2
XS GIS Cut Line= 3
     2216591.514      659491.605     2216999.725      659459.142
2217208.32401855659441.695631911
#Sta/Elev= 30
       0 2229.05    25.2 2221.48    52.8 2210.75    76.5 2206.84    84.9 2201.13
     101 2192.74     113 2191.64   129.1 2185.93   173.2 2175.64   233.4 2164.13
   261.5 2162.05   289.6 2157.73   313.6 2152.06   329.7 2151.47   349.8 2155.28
   377.9 2155.81  392.87 2150.92     410 2149.86   425.4 2150.91   437.7 2154.36
   446.1  2161.9     456 2168.68   474.2 2177.36   498.3 2179.51   510.3 2186.68
   546.4 2198.23   554.5 2199.19   578.5 2206.74   586.6 2207.75   618.8 2220.51
#Mann= 5 ,-1,0
       0      .1       0  392.87    .045       0   425.4      .1       0
   479.5     .06       0   579.5      .1       0
Bank Sta=392.87,425.4
XS Rating Curve= 0 ,0
Exp/Cntr=0.3,0.1

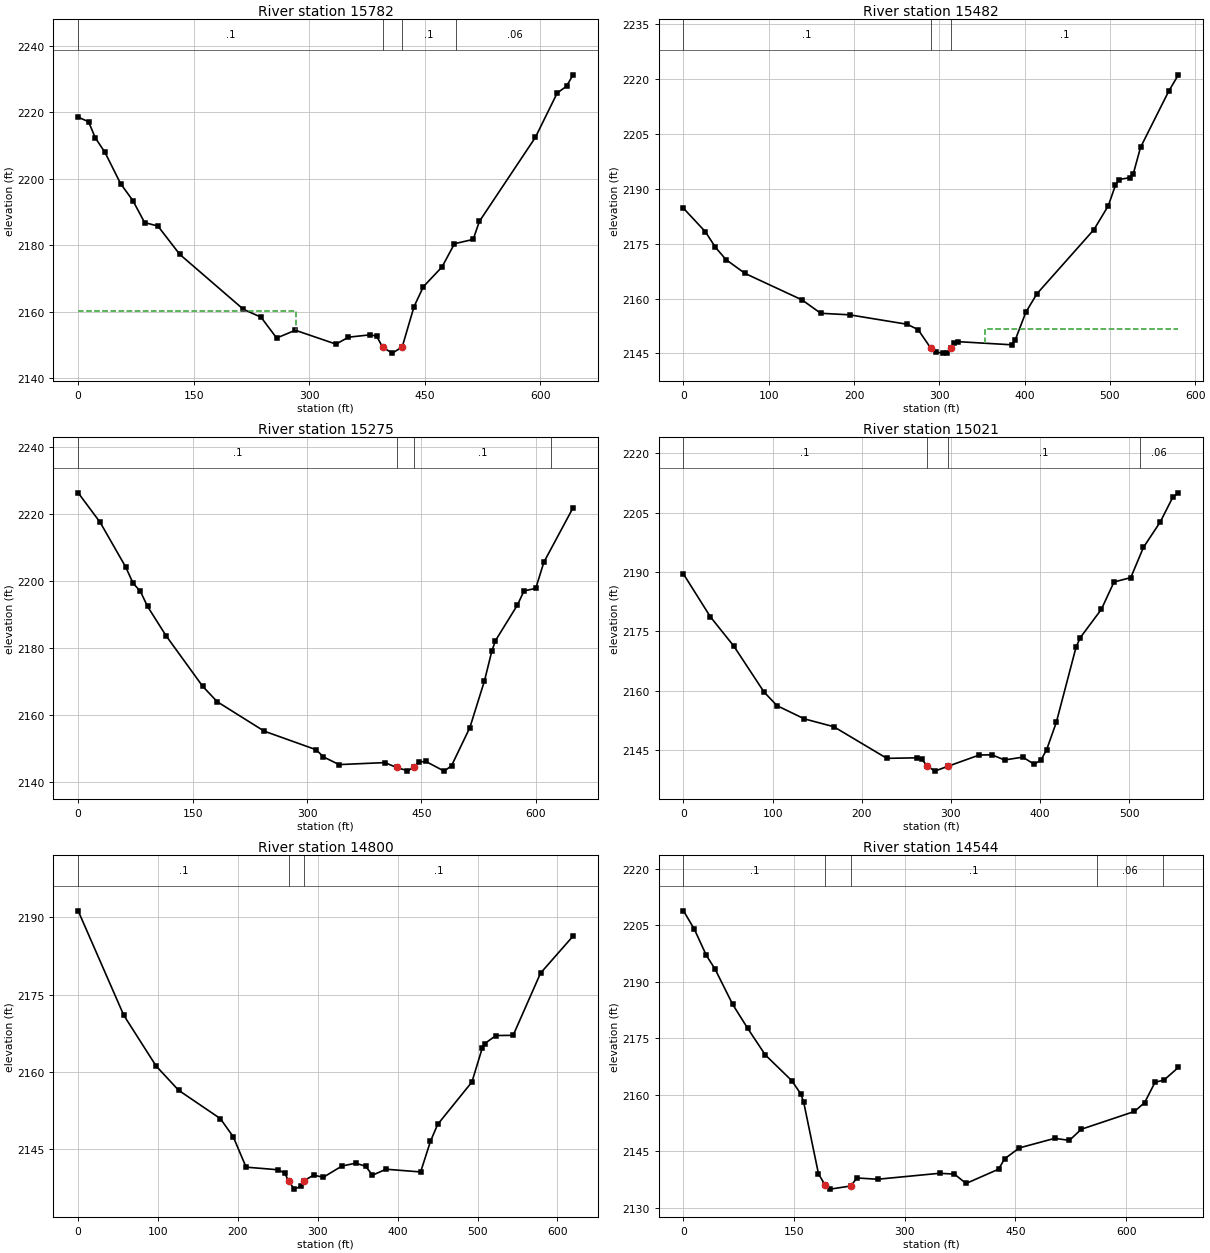
Type RM Length L Ch R = 1 ,15782   ,308.5,300,292.6
XS GIS Cut Line= 3
     2216590.169      659539.614      2216994.46      659608.438
2217224.51312143659641.851812905
#Sta/Elev= 30
       0 2218.59    13.5 2217.18    22.3 2212.32    34.8 2207.97    55.1 2198.55
      71 2193.45    86.3 2186.82   103.5 2185.78   131.9 2177.25   214.6 2160.69
   237.4 2158.33   257.7 2152.05     282 2154.39   334.8 2150.21     351  2152.3
   379.4 2153.02   387.5 2152.62  395.31 2149.31   407.8  2147.5   420.7 2149.32
   436.1 2161.49   448.2 2167.51   472.5 2173.47   488.6 2180.45   512.9 2181.75
     521 2187.19   593.7 2212.49     622 2225.84   634.1 2227.88   642.6 2231.32
#Mann= 4 ,-1,0
       0      .1       0  395.31    .045       0   420.7      .1       0
  490.11     .06       0
#XS Ineff= 2 , 0
          282.41 2160.33
Permanent Ineff=
       F       F
Bank Sta=395.31,420.7
XS Rating Curve= 0 ,0
Exp/Cntr=0.3,0.1

Type RM Length L Ch R = 1 ,15482   ,210.5,207,201.2
XS GIS Cut Line= 3
2216679.81913879659993.324483957     2216966.663      659895.179
2217230.40006793 659809.62978815
#Sta/Elev= 30
       0 2184.67    25.7 2178.25    37.5 2173.99    49.9 2170.63    72.2 2166.86
     139 2159.63     161 2155.97   194.8 2155.55   262.5 2152.96   275.2 2151.49
   290.2 2146.38   296.3 2145.32   304.8 2145.08     309 2145.22  313.72 2146.39
   317.4 2147.72   321.6 2148.22   384.7 2147.36   388.9 2148.58   401.5 2156.24
   414.4 2161.27   481.4 2178.85   498.2 2185.35   506.6 2190.97   510.8 2192.53
   523.4 2193.03   527.6 2194.15     536 2201.31   568.9 2216.59   580.4 2221.14
#Mann= 3 ,-1,0
       0      .1       0   290.2    .045       0  313.72      .1       0
#XS Ineff= 2 , 0
                          353.61         2151.71
Permanent Ineff=
       F       F
Bank Sta=290.2,313.72
XS Rating Curve= 0 ,0
Exp/Cntr=0.3,0.1

Type RM Length L Ch R = 1 ,15275   ,250,253.8,252.6
XS GIS Cut Line= 2
2216744.19289876660271.2045478522217284.93248256659912.857283988
#Sta/Elev= 30
       0 2226.27    28.8 2217.45    62.1 2204.19      72 2199.27    81.6 2196.82
    90.9 2192.34   115.1 2183.61   163.1 2168.49   182.3 2163.85   243.9 2155.06
   311.9 2149.52   321.5 2147.37     342 2145.07   401.9 2145.67   417.5 2144.21
   431.5 2143.25  440.38 2144.21   446.2 2145.85   455.8    2146   479.8 2143.12
   489.4 2144.73   513.4 2156.11   532.5 2170.04   542.2 2178.95     547 2182.12
   575.8 2192.75   584.4 2196.97   599.8 2197.72   610.4 2205.52   648.7 2221.81
#Mann= 4 ,-1,0
       0      .1       0   417.5    .045       0  440.38      .1       0
     620     .06       0
Bank Sta=417.5,440.38
XS Rating Curve= 0 ,0
Exp/Cntr=0.3,0.1

Type RM Length L Ch R = 1 ,15021   ,214.2,221.2,225.6
XS GIS Cut Line= 3
2216916.69073337660353.3406971542217063.67698692660286.373921304
2217397.46685346660077.755254716
#Sta/Elev= 30
       0 2189.47    30.2 2178.66    56.6 2171.22    90.3 2159.68   104.9 2156.22
   135.6 2152.88   168.6  2150.9   228.1 2142.91   261.9 2143.04   267.3 2142.66
   273.1 2141.07   281.8 2139.68   296.3 2140.88   331.9 2143.76   346.1 2143.79
   360.1  2142.5   380.5 2143.21   393.2 2141.46   400.8  2142.4   407.4 2145.14
   418.2 2152.01   440.4 2171.06   445.1 2173.42   468.7 2180.55   482.9 2187.46
   501.7 2188.57   515.9  2196.2   534.8 2202.64   548.9 2208.91   555.1 2209.99
#Mann= 4 ,-1,0
       0      .1       0   273.1    .045       0   296.3      .1       0
  511.52     .06       0
Bank Sta=273.1,296.3
XS Rating Curve= 0 ,0
Exp/Cntr=0.3,0.1

Type RM Length L Ch R = 1 ,14800   ,252.1,255.5,252.8
XS GIS Cut Line= 5
2216951.61896029660436.5793612472217045.79538692660423.466187918
2217271.10354684660397.2398412622217299.71410683660393.663521263
2217550.05650673660295.910774633
#Sta/Elev= 30
       0 2191.26    57.1 2171.01    97.5 2161.19   125.7 2156.47     178 2150.97
   194.1 2147.46   210.2 2141.56   250.5 2141.05   258.6 2140.38   263.8 2138.78
   270.6  2137.3   278.7 2137.83   282.52138.918   294.8 2140.01   306.9  2139.6
   330.1 2141.77   347.2 2142.33   359.8 2141.75   368.4    2140   385.4 2141.16
   428.7 2140.63     441 2146.57     450 2149.85   492.9 2158.07   505.8 2164.64
     509 2165.53     523 2167.08   544.5 2167.12   578.8 2179.18   619.5 2186.36
#Mann= 3 ,-1,0
       0      .1       0   263.8    .045       0   282.5      .1       0
Bank Sta=263.8,282.5
XS Rating Curve= 0 ,0
Exp/Cntr=0.3,0.1

Type RM Length L Ch R = 1 ,14544   ,349.4,349.7,340.7
XS GIS Cut Line= 2
2217005.33924401660635.597759009     2217675.746      660609.548
#Sta/Elev= 30
       0 2208.79    14.8 2203.89    30.9 2197.01    42.9 2193.31    66.7 2183.98
    86.9 2177.67   110.9 2170.59   146.9 2163.74     159 2160.25     163    2158
     183 2139.07     192 2136.04     199    2135     227 2135.84     235 2137.96
   263.2 2137.62   347.1  2139.2   367.3 2138.98   383.1  2136.5   427.2 2140.29
   435.2 2143.01   455.2 2145.92   503.2 2148.46   523.2 2147.93   539.2 2150.87
   611.3 2155.59   625.2 2157.96   639.3 2163.35   651.3  2163.9   670.9 2167.27
#Mann= 5 ,-1,0
       0      .1       0     192    .045       0     227      .1       0
     560     .06       0     650      .1       0
Bank Sta=192,227
XS Rating Curve= 0 ,0
Exp/Cntr=0.3,0.1

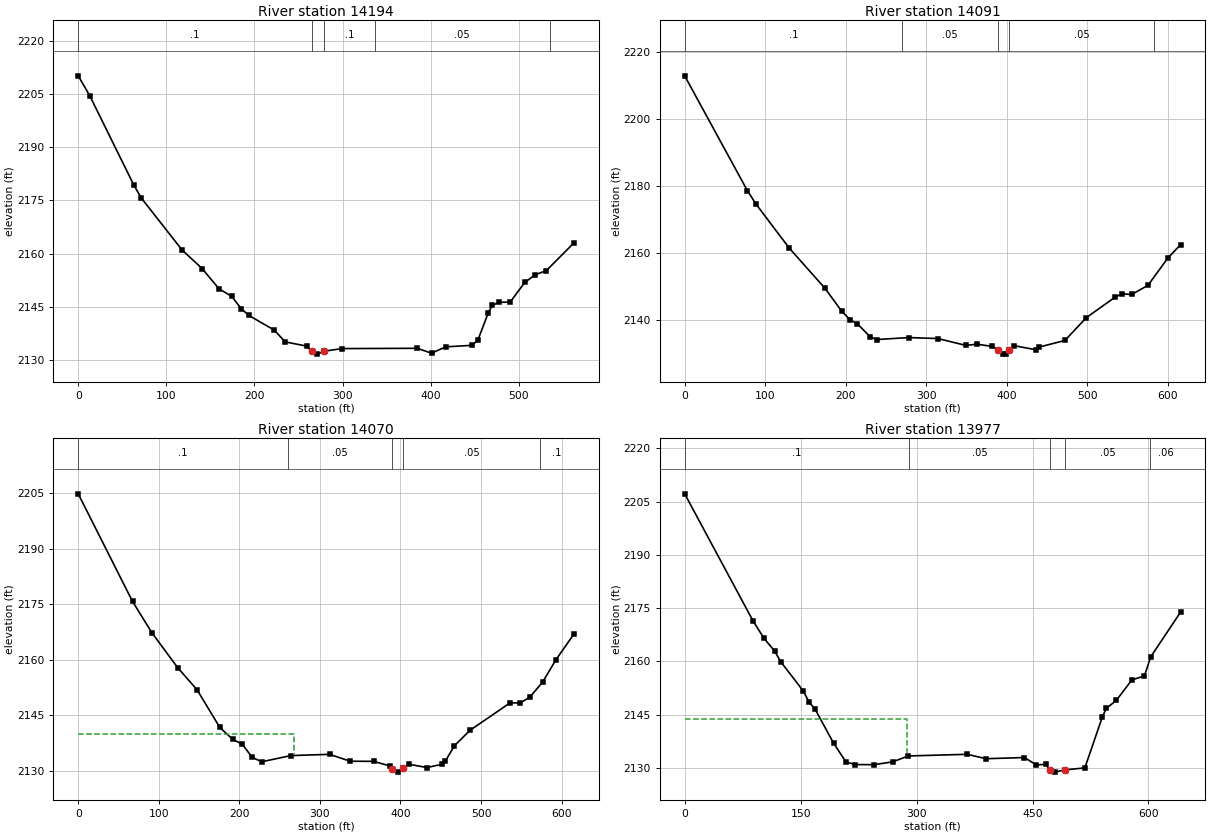
Type RM Length L Ch R = 1 ,14194   ,108.3,103.7,100
XS GIS Cut Line= 4
 2217043.7122469660867.2402230872217259.78432652660934.790302604
2217505.16573706660895.2425823832217590.83499065660915.002342392
#Sta/Elev= 30
       0 2210.08    13.1 2204.48    63.3 2179.23    71.7 2175.64   117.8 2161.06
   140.6 2155.82   159.7 2150.13   174.3 2147.95   184.9 2144.55   193.5 2142.64
   222.6 2138.46   234.9 2135.16   259.2 2133.97  264.87 2132.52   271.3 2131.71
   279.5 2132.55   299.7 2133.27   384.8 2133.35     401 2131.98   417.2 2133.76
   447.1 2134.19   453.7 2135.72   465.4  2143.3   469.9 2145.43     478 2146.31
   490.3 2146.35   506.8 2151.91     519 2154.09   531.4 2155.24   562.9 2163.09
#Mann= 5 ,-1,0
       0      .1       0  264.87    .045       0   279.5      .1       0
  336.38     .05       0  534.93      .1       0
Bank Sta=264.87,279.5
XS Rating Curve= 0 ,0
Exp/Cntr=0.3,0.1

Type RM Length L Ch R = 1 ,14091   ,21.1,21.1,21.1
XS GIS Cut Line= 4
2216994.44011248661007.4170931822217317.97107502661028.467505815
2217466.85164934660948.6421766072217588.49024623660934.704420713
#Sta/Elev= 30
       0 2212.84    77.9 2178.57    88.7 2174.53     130  2161.4   174.1 2149.49
   195.2 2142.56   205.8 2140.01   214.2  2138.9   230.2 2135.04   238.2 2134.19
   278.3 2134.78   314.4 2134.48     349 2132.44     363 2132.81     382 2132.12
  389.13 2131.03   394.8 2129.84   399.2 2129.95     403 2131.05   408.4 2132.38
   435.6 2131.16   440.2 2131.95     472 2133.92   498.5 2140.71   534.7  2146.9
   542.8 2147.79   554.9 2147.64     575 2150.34   599.8  2158.5   615.6 2162.49
#Mann= 5 ,-1,0
       0      .1       0     270     .05       0  389.13    .045       0
     403     .05       0  583.15      .1       0
Bank Sta=389.13,403
XS Rating Curve= 0 ,0
Exp/Cntr=0.3,0.1

Type RM Length L Ch R = 1 ,14070   ,92.6,92.7,93.1
XS GIS Cut Line= 4
2217004.87756404661025.7030148682217328.40852658661046.753427501
 2217477.2891009660966.9280982932217598.92769779660952.990342399
#Sta/Elev= 30
       0 2204.79    67.4 2175.77    91.5 2167.31   123.6 2157.86   147.6 2151.91
   175.7 2141.79   191.7 2138.58   203.7 2137.24   215.8 2133.73   227.8 2132.51
   263.9 2134.18     312 2134.52   337.6 2132.66   366.6 2132.63   386.8  2131.4
  389.76 2130.68   396.6 2129.72   403.7  2130.7   410.2 2131.85   432.9 2130.96
     451 2131.82   455.6 2132.64     467 2136.83   486.1 2140.97   536.3 2148.44
   548.4 2148.35   560.5 2149.93   576.6 2154.04   592.7 2159.94   615.6 2167.05
#Mann= 5 ,-1,0
       0      .1       0     260     .05       0  389.76    .045       0
   403.7     .05       0  573.15      .1       0
#XS Ineff= 2 , 0
          267.77  2140.1
Permanent Ineff=
       F       F
Bank Sta=389.76,403.7
XS Rating Curve= 0 ,0
Exp/Cntr=0.3,0.1

Type RM Length L Ch R = 1 ,13977   ,489.9,502.7,511.7
XS GIS Cut Line= 4
2216976.42929795661068.6527186472217402.44596568661112.081549569
2217510.44866579661050.601746239 2217598.4279572661064.775720644
#Sta/Elev= 30
       0  2207.2    88.2  2171.5   102.4 2166.56   116.3 2162.93   124.3 2159.89
   153.5 2151.65   160.8 2148.55   168.6 2146.58   192.7 2136.93   208.8 2131.64
   220.9 2130.93     245  2130.9   269.1 2131.69   289.2 2133.36   365.6 2133.82
   389.8 2132.58   439.4 2132.91   455.1 2130.83     467    2131   472.7 2129.41
   478.5  2128.8  492.07 2129.44   517.7 2129.99   540.1  2144.2   545.3 2146.73
   558.3 2148.99   578.6 2154.78   594.8 2155.91   602.9 2161.27   641.6 2173.89
#Mann= 5 ,-1,0
       0      .1       0     290     .05       0   472.7    .045       0
  492.07     .05       0   602.5     .06       0
#XS Ineff= 2 , 0
          286.99 2143.74
Permanent Ineff=
       F       F
Bank Sta=472.7,492.07
XS Rating Curve= 0 ,0
Exp/Cntr=0.3,0.1