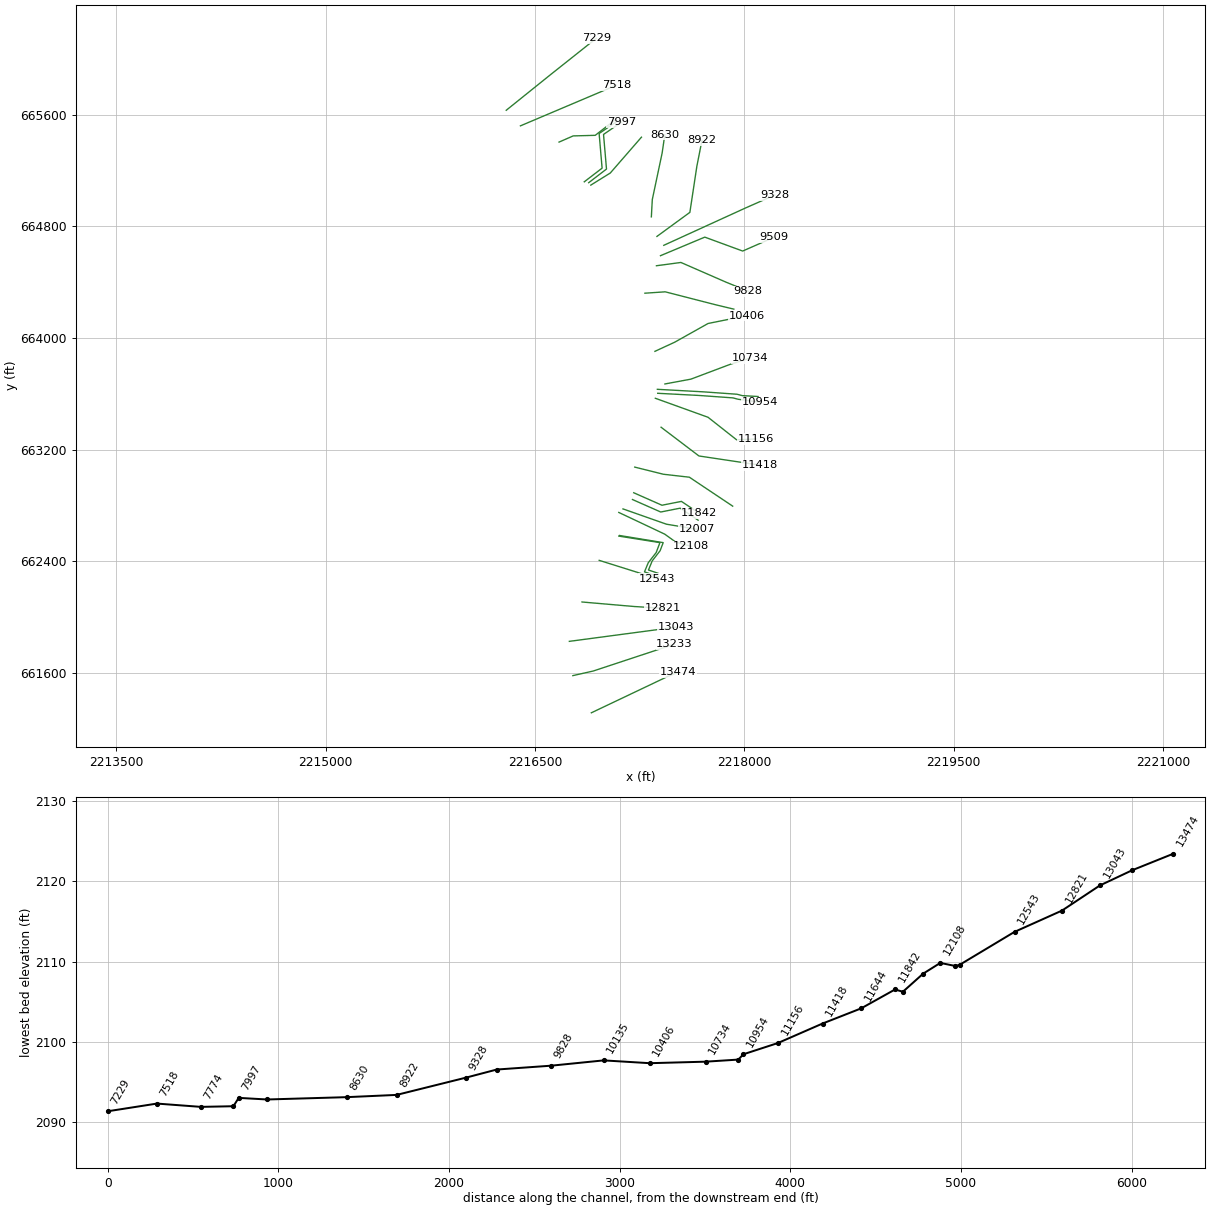
HEC-RAS study JENKSFK.prj: JENKSFK

--- JENKSFK.g01 (geometry) --- (continued)

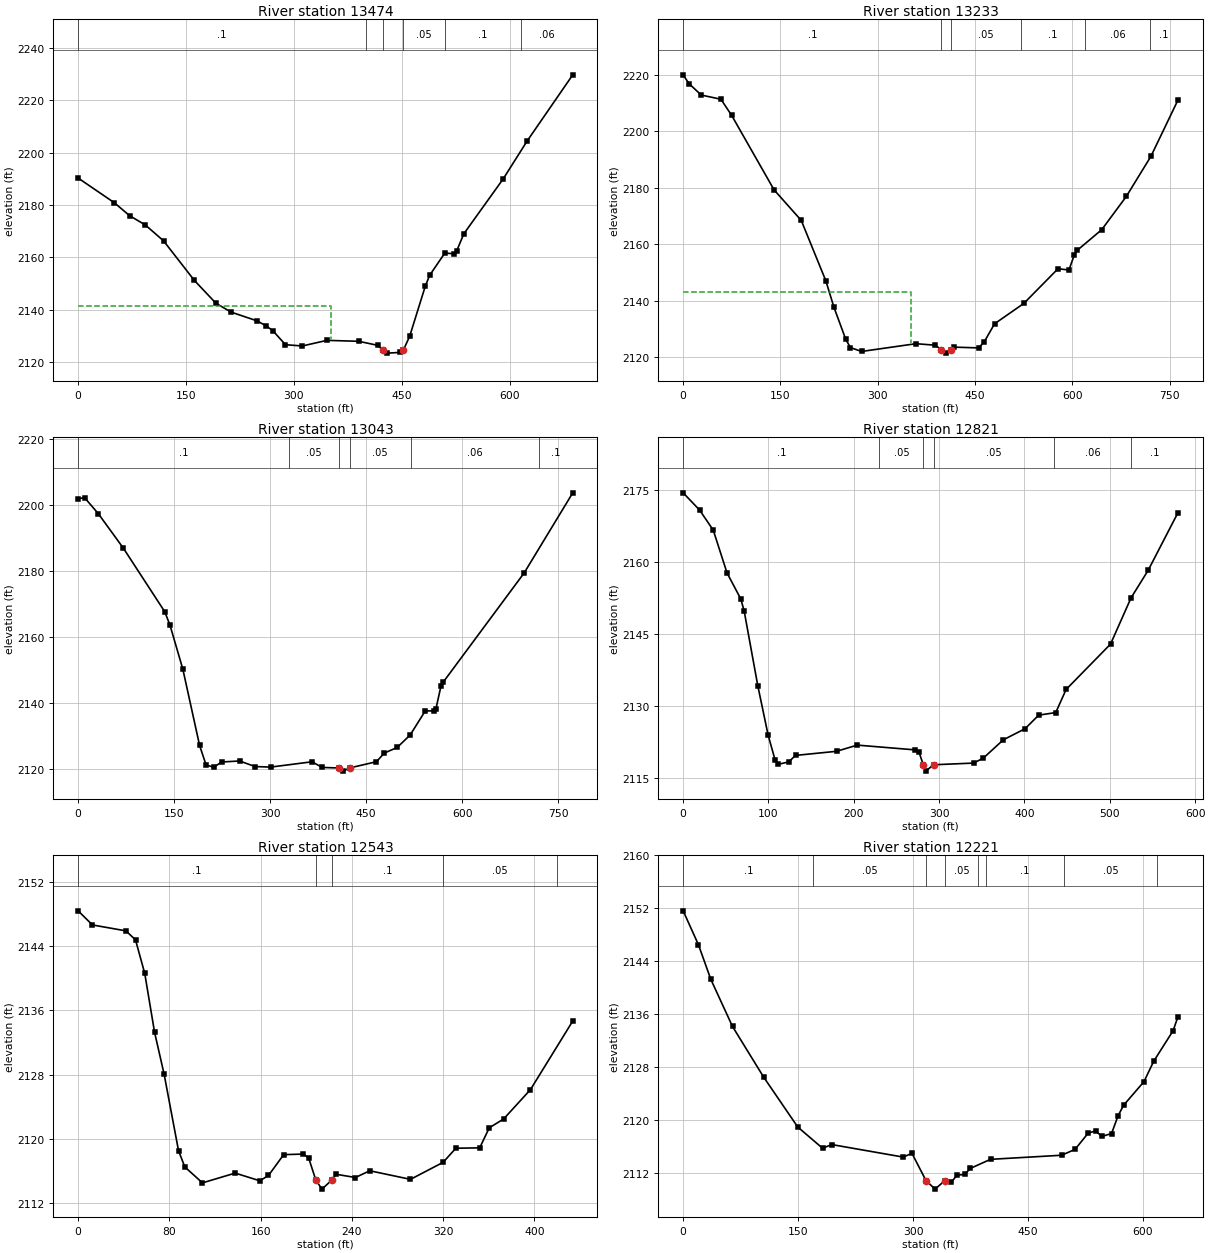
Type RM Length L Ch R = 1 ,13474   ,243.1,241.2,242.7
XS GIS Cut Line= 3
     2216903.909      661314.2012217450.54699457661574.159341058
2217526.72261054661605.273325046
#Sta/Elev= 30
       0 2190.36    50.5 2180.89    71.5 2175.98    93.3 2172.45   118.7 2166.37
   161.5 2151.26   191.5 2142.52   212.6 2139.13   248.6 2135.79   260.6 2133.99
   270.5 2132.07   288.2 2126.67   311.6 2126.18   345.8 2128.33   390.1 2127.97
   416.7 2126.41  423.62 2124.56   429.9 2123.45   447.7 2123.72   452.1 2124.61
   460.9  2129.9   482.7 2149.14   488.7  2153.2   509.7 2161.69   522.9 2161.42
   526.4 2162.62   536.2 2169.07   590.8    2190   624.3 2204.57   687.6 2229.81
#Mann= 6 ,-1,0
       0      .1       0     400     .05       0  423.62    .045       0
   452.1     .05       0     510      .1       0   615.3     .06       0
#XS Ineff= 2 , 0
          352.17 2141.41
Permanent Ineff=
       F       F
Bank Sta=423.62,452.1
XS Rating Curve= 0 ,0
Exp/Cntr=0.3,0.1

Type RM Length L Ch R = 1 ,13233   ,191.9,189.9,187.4
XS GIS Cut Line= 3
      2216771.39      661580.5472216917.97090032661613.704752533
2217499.45404084 661805.76638209
#Sta/Elev= 30
       0 2219.94       9 2216.82    27.9 2212.78    58.2  2211.3    74.6 2205.65
   140.2  2179.2   182.1 2168.39     220 2147.01   232.6 2137.58   250.6 2126.35
   257.9 2123.35   275.1 2121.98     359 2124.73   388.5  2124.2   398.22122.644
   405.4 2121.39   413.22122.528     418 2123.51   455.6 2123.24   464.3 2125.41
   480.2 2131.78   525.3 2138.99   578.1 2151.29   594.9 2150.81   603.3 2156.28
   607.6 2157.78   645.5 2165.12   683.4 2176.89   721.3 2191.08   762.7 2210.87
#Mann= 6 ,-1,0
       0      .1       0   398.2    .045       0   413.2     .05       0
  520.28      .1       0  620.28     .06       0  720.28      .1       0
#XS Ineff= 2 , 0
             352 2142.86
Permanent Ineff=
       F       F
Bank Sta=398.2,413.2
XS Rating Curve= 0 ,0
Exp/Cntr=0.3,0.1

Type RM Length L Ch R = 1 ,13043   ,223.1,222,218.6
XS GIS Cut Line= 2
2216746.04725185661826.091955536 2217512.2214815661928.022518499
#Sta/Elev= 30
       0  2201.9    10.2 2202.14    31.5 2197.34    70.7 2186.89   135.3  2167.7
   143.4 2163.69   163.6 2150.32   189.8 2127.24   199.9 2121.35     212 2120.67
   224.1 2122.25   252.3 2122.56   276.5 2120.87   300.8 2120.71   365.3 2122.31
   381.5 2120.61   407.3 2120.43   414.2 2119.49  424.21 2120.45   466.2 2122.34
   478.3 2124.94   498.5 2126.64   518.7 2130.39   542.4 2137.68   556.7 2137.72
     559 2138.27   567.1 2145.31   570.9 2146.51   697.1 2179.46   772.9 2203.64
#Mann= 6 ,-1,0
       0      .1       0     330     .05       0   407.3    .045       0
  424.21     .05       0     520     .06       0     720      .1       0
Bank Sta=407.3,424.21
XS Rating Curve= 0 ,0
Exp/Cntr=0.3,0.1

Type RM Length L Ch R = 1 ,12821   ,279.6,277.9,273.6
XS GIS Cut Line= 3
2216836.96269028 662108.158446442217210.74796198662075.777801435
2217414.88681092662063.107114259
#Sta/Elev= 30
       0 2174.44    19.3 2170.84    35.3 2166.64    51.4 2157.73    67.5 2152.31
    71.5 2149.78    87.5 2134.16    99.6 2123.86   107.6 2118.78   111.6 2117.79
   123.7 2118.28   131.7 2119.64   179.9  2120.5     204 2121.79   272.2 2120.79
   276.2 2120.43  281.45 2117.69   284.3 2116.36   293.52117.688   340.5 2118.04
   351.9 2119.09   375.2 2122.89   400.7 2125.21   416.7 2128.04   436.7 2128.58
   448.8  2133.4   500.9 2142.87   524.9 2152.51     545 2158.27   579.7 2170.22
#Mann= 6 ,-1,0
       0      .1       0     230     .05       0  281.45    .045       0
   293.5     .05       0  435.19     .06       0  525.19      .1       0
Bank Sta=281.45,293.5
XS Rating Curve= 0 ,0
Exp/Cntr=0.3,0.1

Type RM Length L Ch R = 1 ,12543   ,341.9,322.1,282.3
XS GIS Cut Line= 2
2216960.22954513662406.4336776922217374.04048824662276.449287943
#Sta/Elev= 30
       0 2148.42    12.5 2146.66    41.9 2145.92    50.3  2144.8    58.4 2140.61
      67 2133.28    75.4 2128.03      88 2118.52    93.5 2116.48     109 2114.49
   137.7 2115.71   159.3 2114.75   166.9 2115.41   180.2 2118.01     197 2118.08
     202 2117.65  208.43 2114.83   213.8 2113.71   222.62114.866   226.3 2115.56
   243.1 2115.16   255.7    2116   291.4 2114.93     320 2117.05   331.2 2118.81
   352.1 2118.86   360.5 2121.36   373.1 2122.46   396.6 2126.12   433.7 2134.68
#Mann= 5 ,-1,0
       0      .1       0  208.43    .045       0   222.6      .1       0
     320     .05       0     420     .06       0
Bank Sta=208.43,222.6
XS Rating Curve= 0 ,0
Exp/Cntr=0.3,0.1

Type RM Length L Ch R = 1 ,12221   ,27,25.1,36.2
XS GIS Cut Line= 6
2217100.53460473662580.2995115412217395.39539755 662533.50887496
2217368.31765471662462.213491803 2217311.6431398662389.363623231
2217284.67366909662323.9419257932217385.89085657662289.053979282
#Sta/Elev= 30
       0 2151.64    19.9 2146.53    36.1 2141.29    64.4 2134.17   104.9 2126.55
   149.5 2118.99   181.9 2115.78     194 2116.33   287.2 2114.44   298.6 2115.01
   316.9 2110.89   328.8  2109.6   341.6  2110.9   350.2 2110.65   357.2 2111.71
   367.4 2111.82   374.8 2112.73   401.1  2114.1     494 2114.72   511.5 2115.61
   528.7 2118.08   538.4 2118.39   546.4 2117.56   559.1    2118   567.5 2120.66
   574.8 2122.27   601.4 2125.84   614.1 2128.92   639.4 2133.53   645.5 2135.56
#Mann= 8 ,-1,0
       0      .1       0     170     .05       0   316.9    .045       0
   341.6     .05       0  384.82     .06       0  394.82      .1       0
  497.59     .05       0  618.42     .06       0
Bank Sta=316.9,341.6
XS Rating Curve= 0 ,0
Exp/Cntr=0.3,0.1

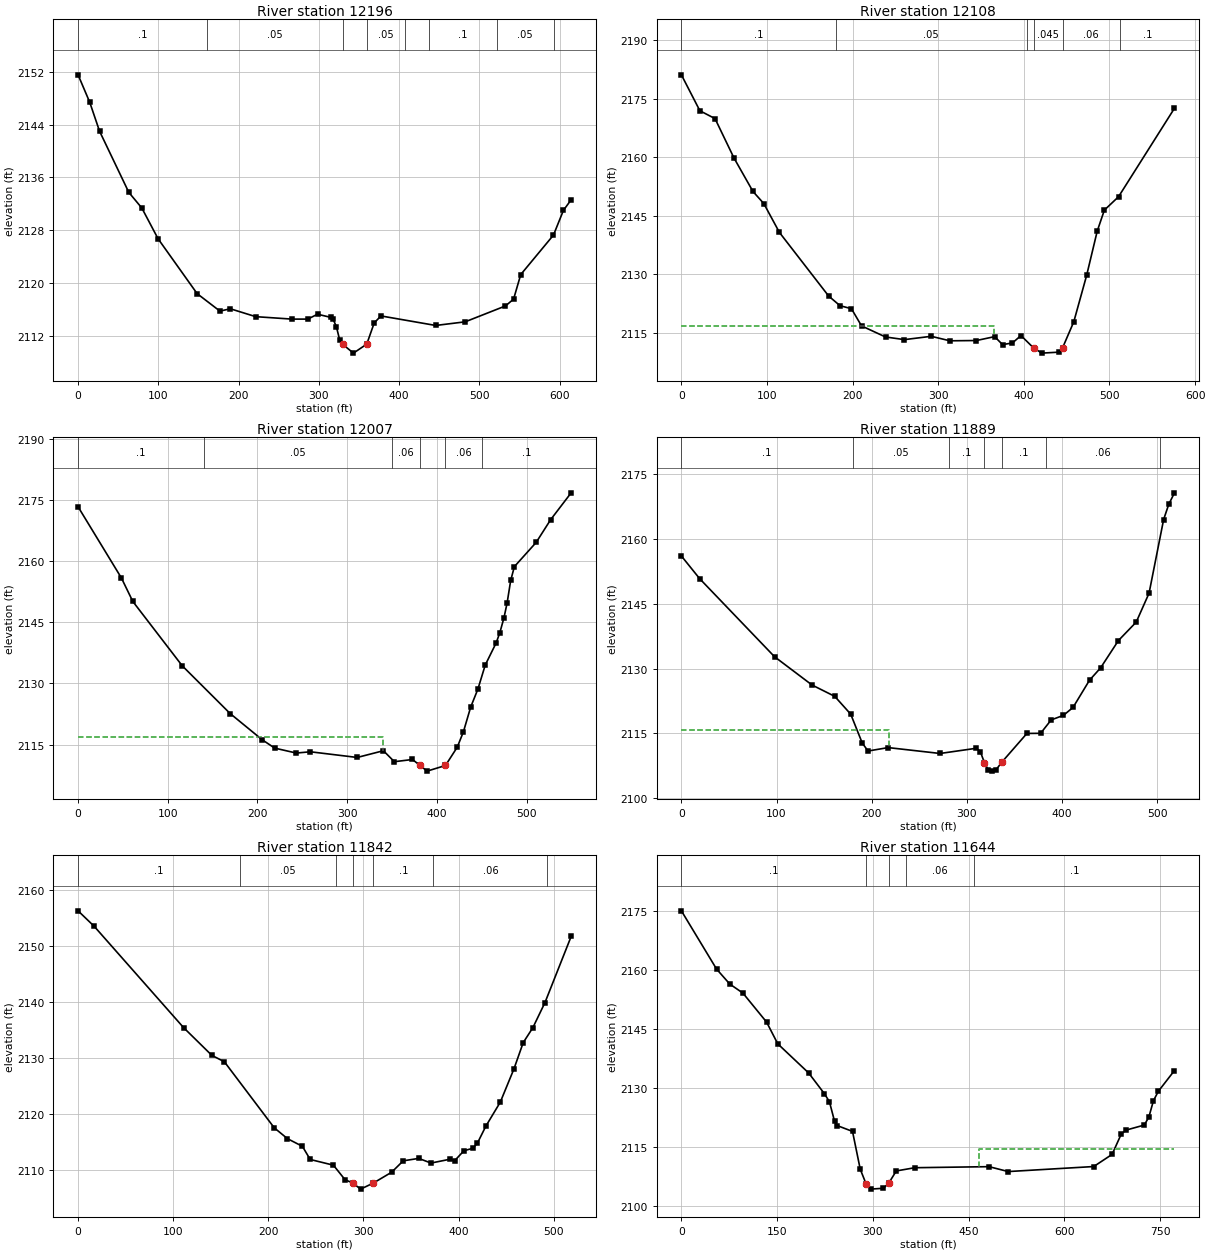
Type RM Length L Ch R = 1 ,12196   ,62.2,88,114.4
XS GIS Cut Line= 6
2217105.80231941662584.7387396252217418.69405201 662533.47057188
2217396.76191589662475.6560395862217340.08740098662402.806171014
2217313.11793027662337.3844735762217381.01277905662314.320582734
#Sta/Elev= 30
       0 2151.51    14.6 2147.34    26.7 2143.01    63.2 2133.75    79.4 2131.39
    99.7 2126.73   148.3 2118.45   176.7 2115.81   189.7 2116.16   221.3 2114.97
   266.4  2114.6   286.1  2114.6   298.3 2115.34   314.5 2114.87   317.4 2114.65
   321.7 2113.48   325.9 2111.44  329.46 2110.81     343 2109.46   359.6 2110.82
   368.9 2114.03   377.3 2115.08   445.5 2113.64   482.2 2114.19   532.4 2116.59
   542.5 2117.62   551.4 2121.33   592.2  2127.3   604.6 2131.04   614.2 2132.63
#Mann= 8 ,-1,0
       0      .1       0     160     .05       0  329.46    .045       0
   359.6     .05       0  407.24     .06       0  437.24      .1       0
  521.66     .05       0   592.5     .06       0
Bank Sta=329.46,359.6
XS Rating Curve= 0 ,0
Exp/Cntr=0.3,0.1

Type RM Length L Ch R = 1 ,12108   ,92.7,100.6,112.3
XS GIS Cut Line= 4
2217100.61059888662749.7627224882217429.53432933662594.437627554
2217509.61543364662536.9297204332217619.25667712662507.369581259
#Sta/Elev= 30
       0 2181.16    21.6 2171.95    39.3 2169.94    61.4 2159.86    83.6 2151.27
    96.3 2148.16   114.5 2140.77     172 2124.47   185.3 2121.99   198.6 2121.23
   210.4 2116.82   238.4 2113.98   260.5  2113.3   291.8 2114.15   313.6    2113
   344.6 2113.07   365.9 2114.07   375.1 2112.02   386.7 2112.45   396.6 2114.35
   411.3 2111.18     421 2109.84   440.9 2110.09  445.14 2111.16   458.3 2117.87
   473.3 2129.75   485.7 2141.12     494 2146.48   510.6 2149.93   575.9 2172.59
#Mann= 6 ,-1,0
       0      .1       0     180     .05       0  403.75     .06       0
   411.3    .045       0  445.14     .06       0  512.34      .1       0
#XS Ineff= 2 , 0
          365.54  2116.9
Permanent Ineff=
       F       F
Bank Sta=411.3,445.14
XS Rating Curve= 0 ,0
Exp/Cntr(USF)=0,0
Exp/Cntr=0.3,0.1

Type RM Length L Ch R = 1 ,12007   ,113.7,118.4,125.2
XS GIS Cut Line= 3
2217130.61331189662775.095006388 2217442.1218057662665.551060331
2217658.60550879662629.508739133
#Sta/Elev= 30
       0 2173.28    48.3 2155.84      61 2150.09   116.1 2134.32   169.5 2122.62
   205.2  2116.2   219.2 2114.14   243.3 2112.93     259 2113.24   311.2 2111.85
   340.4  2113.5   352.6 2110.81   372.8 2111.35   381.2  2109.9   389.1  2108.5
   409.62109.881   422.7 2114.36   429.6 2118.14   437.7 2124.19   445.8 2128.64
   453.9 2134.48   466.1 2139.93   470.2 2142.42   474.8 2146.08   478.3  2149.7
   482.3 2155.22   486.4 2158.61   510.7 2164.55   526.9 2170.14   549.7  2176.7
#Mann= 6 ,-1,0
       0      .1       0     140     .05       0  350.21     .06       0
   381.2    .045       0   409.6     .06       0  450.21      .1       0
#XS Ineff= 2 , 0
          339.48 2116.77
Permanent Ineff=
       F       F
Bank Sta=381.2,409.6
XS Rating Curve= 0 ,0
Exp/Cntr=0.3,0.1

Type RM Length L Ch R = 1 ,11889   ,47.6,46.4,47.1
XS GIS Cut Line= 4
2217198.58994578662842.3501379452217400.96330235662752.881257385
2217540.41924709662780.4464303572217669.12416197  662694.3212503
#Sta/Elev= 30
       0 2156.08    19.2 2150.83    97.9 2132.75   137.3  2126.2   161.2 2123.57
     178 2119.44   190.1 2112.76   196.2 2110.91   217.4  2111.7   271.9 2110.34
   310.2 2111.55   314.2 2110.78   318.5 2108.24   322.4 2106.59   326.5 2106.25
   330.6 2106.51   336.6 2108.27   363.2 2114.98   377.6 2115.01   388.7 2118.11
   401.6 2119.17   411.7 2121.01     429 2127.31   440.6 2130.15   459.4  2136.5
   478.1 2140.77   491.6 2147.47   506.9 2164.52   512.3 2168.05   518.3 2170.71
#Mann= 7 ,-1,0
       0      .1       0     180     .05       0  281.27      .1       0
   318.5    .045       0   336.6      .1       0  383.42     .06       0
  503.42      .1       0
#XS Ineff= 2 , 0
          217.71 2115.76
Permanent Ineff=
       F       F
Bank Sta=318.5,336.6
XS Rating Curve= 0 ,0
Exp/Cntr=0.3,0.1

Type RM Length L Ch R = 1 ,11842   ,203.5,198.1,194.4
XS GIS Cut Line= 4
  2217207.548339662890.8640760232217409.92169557662801.395195463
2217549.37764031662828.9603684352217678.08255519662742.835188378
#Sta/Elev= 30
       0 2156.27    16.9 2153.51   110.9  2135.4   140.6 2130.44   153.8 2129.29
   206.2 2117.49   220.1 2115.55   235.8 2114.18     244 2111.83   268.4 2110.81
   280.6 2108.22   288.8 2107.62     297 2106.53  310.31 2107.61   329.6 2109.55
   341.8 2111.59   358.1 2112.02     371 2111.19   390.9 2111.87   395.7 2111.59
   405.6 2113.39   414.9 2113.83   419.7 2114.73   428.7  2117.8   443.8 2122.07
   458.2 2128.03   467.9 2132.71   478.1  2135.4   490.8 2139.88   518.3 2151.69
#Mann= 7 ,-1,0
       0      .1       0     170     .05       0  271.27      .1       0
   288.8    .045       0  310.31      .1       0  373.42     .06       0
  493.42      .1       0
Bank Sta=288.8,310.31
XS Rating Curve= 0 ,0
Exp/Cntr=0.3,0.1

Type RM Length L Ch R = 1 ,11644   ,237.5,226.4,216.1
XS GIS Cut Line= 4
  2217214.672775663074.696056251 2217419.9521347663023.520284823
2217606.37210719663002.2618669072217916.77768542662794.944440837
#Sta/Elev= 30
       0 2175.15    55.1  2160.3    75.8 2156.48    96.4 2154.17   133.5 2146.77
     151 2141.23   199.4  2133.8   223.9 2128.55   231.9 2126.49     240 2121.45
     244 2120.39   268.1  2118.9   280.2 2109.26  289.17  2105.6   296.3 2104.18
   316.5  2104.4   324.5 2105.62   336.7 2108.82   365.7 2109.64     482 2109.91
     512 2108.66     646 2109.94   674.8 2113.04   689.2 2118.25   696.4 2119.22
   725.2 2120.52   732.4 2122.56   739.6 2126.75   747.3 2129.14   772.5 2134.43
#Mann= 5 ,-1,0
       0      .1       0  289.17    .045       0   324.5      .1       0
  351.56     .06       0  459.19      .1       0
#XS Ineff= 2 , 0
                          466.42         2114.43
Permanent Ineff=
       F       F
Bank Sta=289.17,324.5
XS Rating Curve= 0 ,0
Exp/Cntr=0.3,0.1

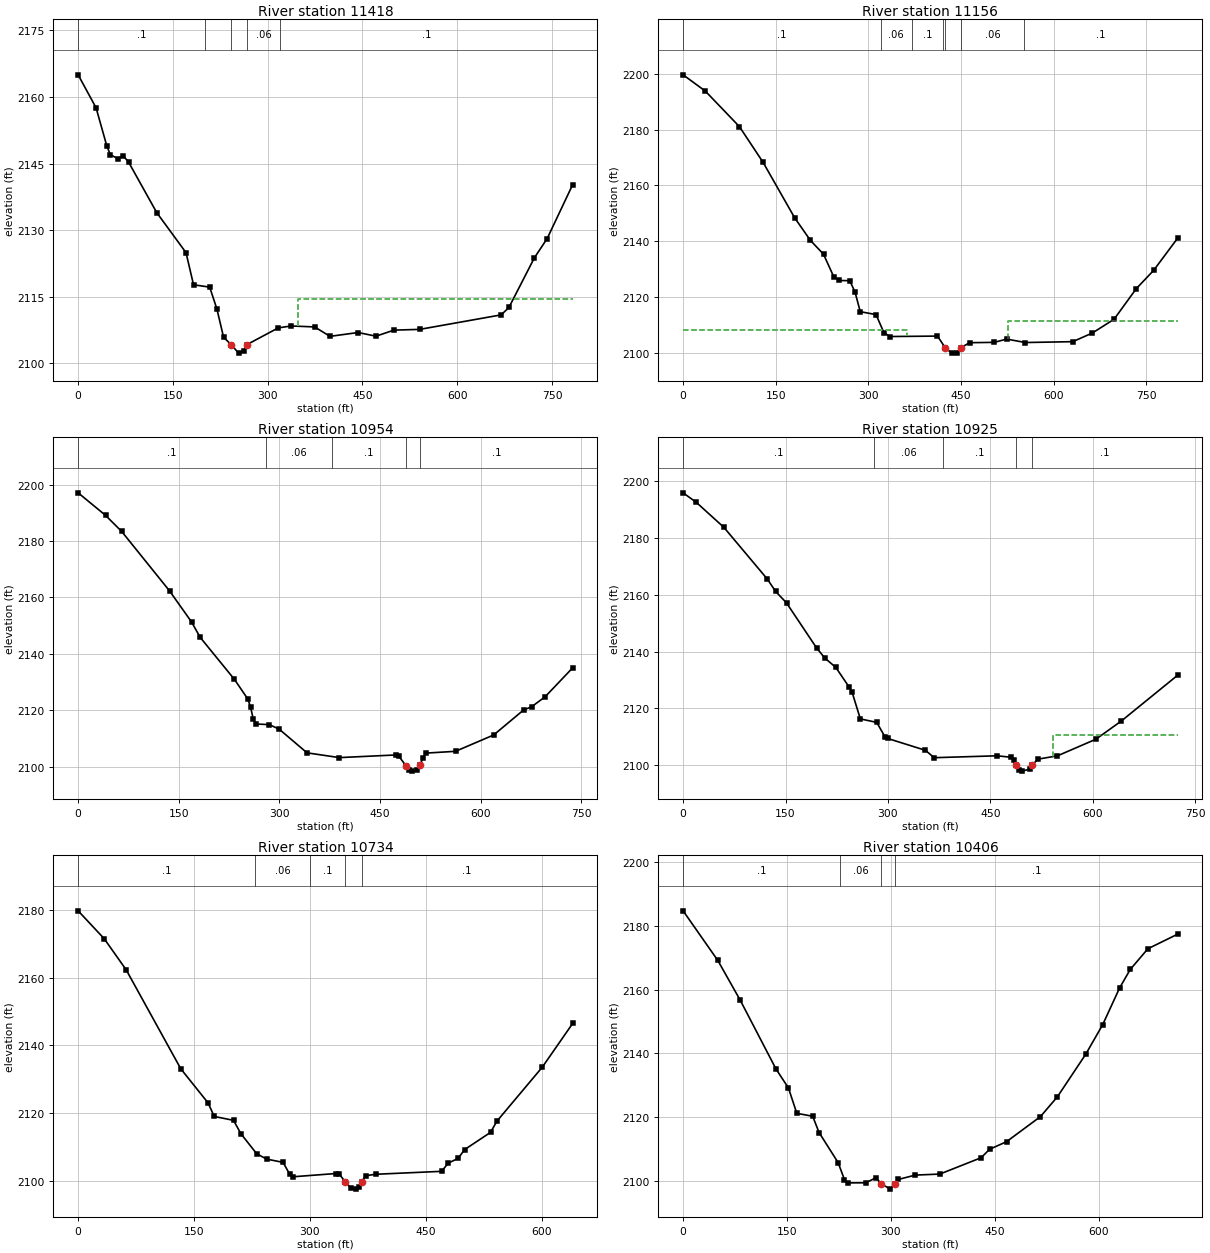
Type RM Length L Ch R = 1 ,11418   ,261.7,261.8,260.8
XS GIS Cut Line= 3
2217403.59950553663360.3844456472217675.05314969663154.341318152
 2218112.1058175663088.943718747
#Sta/Elev= 30
       0 2164.99    28.4 2157.55    45.5  2148.9    50.9 2147.03    62.7 2146.09
    71.2 2146.79    79.8 2145.33   124.4 2133.94   170.7 2124.93   182.6 2117.69
   208.2 2117.16   219.7 2112.17   230.2 2105.84   242.5 2104.17   253.9 2102.29
   261.9 2102.77   266.9 2104.19   316.7 2107.98   337.2 2108.41   374.3 2108.19
   398.6 2106.07     443 2106.93   471.4 2106.11   499.7 2107.47   540.5 2107.64
   669.5 2110.91   681.7 2112.57   722.1 2123.78   742.3 2128.11   782.7 2140.27
#Mann= 5 ,-1,0
       0      .1       0     200     .06       0   242.5    .045       0
   266.9     .06       0     320      .1       0
#XS Ineff= 2 , 0
                          347.49         2114.51
Permanent Ineff=
       F       F
Bank Sta=242.5,266.9
XS Rating Curve= 0 ,0
Exp/Cntr=0.3,0.1

Type RM Length L Ch R = 1 ,11156   ,191.4,202.2,210.4
XS GIS Cut Line= 4
     2217362.353      663567.8782217740.08966065663431.698586422
2217945.15207093663270.0015046912218083.03016945663276.103078542
#Sta/Elev= 30
       0 2199.63      36 2193.79    91.2 2181.05   129.5 2168.25   180.5 2148.41
     206  2140.3   227.3 2135.32   243.8 2127.28   252.8  2125.9   269.8 2125.82
   278.3 2121.77   286.8 2114.72   312.3 2113.68   325.1  2107.2   334.8 2105.81
   411.8 2105.97   424.42101.776   434.7 2099.86   443.3    2100  449.66 2101.77
   463.7  2103.6   503.5 2103.72   523.9 2104.89   554.3 2103.66   630.9 2103.97
   662.7 2107.09   697.7    2112   733.7 2122.98   761.8 2129.53   800.7  2141.1
#Mann= 7 ,-1,0
       0      .1       0     320     .06       0     370      .1       0
  421.53     .06       0   424.4    .045       0  449.66     .06       0
  551.53      .1       0
#XS Ineff= 2 , 0
          362.93  2108.2  525.34         2111.23
Permanent Ineff=
       F       F
Bank Sta=424.4,449.66
XS Rating Curve= 0 ,0
Exp/Cntr=0.3,0.1

Type RM Length L Ch R = 1 ,10954   ,29.1,29.4,28.2
XS GIS Cut Line= 5
     2217379.457      663603.5732217677.46872634663587.908377773
2217918.93864854663570.6366926972217955.80127377663560.806659302
2218112.88830378663539.644420527
#Sta/Elev= 30
       0 2197.07    40.8 2189.09    64.8 2183.41   136.2 2162.34     169 2151.33
   181.8 2145.89     233 2130.95   253.1 2123.94   257.1 2121.03   261.1 2116.87
   265.1 2115.16   285.1 2114.93   299.8  2113.3   341.2 2104.94   389.4 2103.25
   473.6 2104.19   477.6 2103.89   488.4 2100.43   493.6 2098.73   497.6 2098.46
   505.7 2098.71   509.8 2100.48   513.7 2103.16   518.7 2104.85   562.5 2105.48
   619.4 2111.27     664 2120.13   675.9 2121.26   696.1 2124.81   737.2 2135.08
#Mann= 5 ,-1,0
       0      .1       0     280     .06       0  378.42      .1       0
   488.4    .045       0   509.8      .1       0
Bank Sta=488.4,509.8
XS Rating Curve= 0 ,0
Exp/Cntr=0.3,0.1

Type RM Length L Ch R = 1 ,10925   ,184.4,190.9,199.3
XS GIS Cut Line= 5
2217376.92073444663632.0910826192217706.88006931663613.968952043
2217948.34999151663596.6972669672217985.21261674663586.867233572
2218098.88366592663580.450044891
#Sta/Elev= 30
       0 2195.98    19.3 2192.62    59.7 2183.81   123.3 2165.57   135.5 2161.21
   151.5 2157.14   195.5 2141.27   207.6 2137.68   223.6 2134.42   243.6 2127.32
   247.6  2125.6   259.6 2116.23   283.7 2114.99   295.7 2109.88   299.7 2109.32
   354.9 2105.15   367.8 2102.54   460.1 2103.21   480.1  2102.7   484.1 2101.82
  487.34 2100.13   492.2 2098.15   496.2  2097.8   508.1  2098.5  511.72 2100.13
   520.2 2102.05   548.3 2103.19   604.7 2109.06   641.8 2115.45   724.5 2131.64
#Mann= 5 ,-1,0
       0      .1       0     280     .06       0  380.46      .1       0
  487.34    .045       0  511.72      .1       0
#XS Ineff= 2 , 0
                           542.5         2110.56
Permanent Ineff=
       F       F
Bank Sta=487.34,511.72
XS Rating Curve= 0 ,0
Exp/Cntr=0.3,0.1

Type RM Length L Ch R = 1 ,10734   ,325,328.1,329.2
XS GIS Cut Line= 4
2217430.98892826 663670.392594312217617.26156586 663704.89031045
 2217900.0977512663811.4725108812218041.85736054663855.506615954
#Sta/Elev= 30
       0 2179.79    33.8 2171.53    62.2 2162.34   132.8 2133.12   168.2 2123.01
   176.1 2119.02   201.1 2117.87   210.6 2113.93     231 2108.02   243.8 2106.42
   265.2 2105.45   273.8 2101.95     278 2101.19   333.6 2102.15   337.9    2102
  345.82 2099.67   353.4 2097.78   359.3 2097.54   363.5 2098.07  367.01 2099.65
     372 2101.49   384.9 2101.93   470.4  2102.8     479 2105.23   491.8 2106.62
   500.1 2109.21   533.7 2114.31     542 2117.63   600.7 2133.58   640.1 2146.53
#Mann= 5 ,-1,0
       0      .1       0  229.44     .06       0  299.44      .1       0
  345.82    .045       0  367.01      .1       0
Bank Sta=345.82,367.01
XS Rating Curve= 0 ,0
Exp/Cntr=0.3,0.1

Type RM Length L Ch R = 1 ,10406   ,277.7,270.1,254.5
XS GIS Cut Line= 4
2217359.48440231663904.1730951172217501.10667425663969.619751092
2217740.36248216664103.7317510422218018.26184801664159.737208001
#Sta/Elev= 30
       0  2184.8    50.1  2169.2    82.6 2156.65   133.9 2135.16     152 2129.14
   164.1 2121.17     187 2120.25   196.2 2115.14   223.7 2105.69   232.9 2100.31
   237.5 2099.31   263.7 2099.34   278.4 2100.94     286 2099.02     299 2097.35
  305.95 2099.01   310.7  2100.4   335.1 2101.76   370.5 2102.08   430.1 2107.22
   442.3 2109.86   466.8 2112.26   515.8 2120.15   540.3  2126.4   581.1 2139.74
   605.6 2149.04     630 2160.58   645.3 2166.37   670.8 2172.88   713.8 2177.47
#Mann= 4 ,-1,0
       0      .1       0  226.01     .06       0     286    .045       0
  305.95      .1       0
Bank Sta=286,305.95
XS Rating Curve= 0 ,0
Exp/Cntr=0.3,0.1

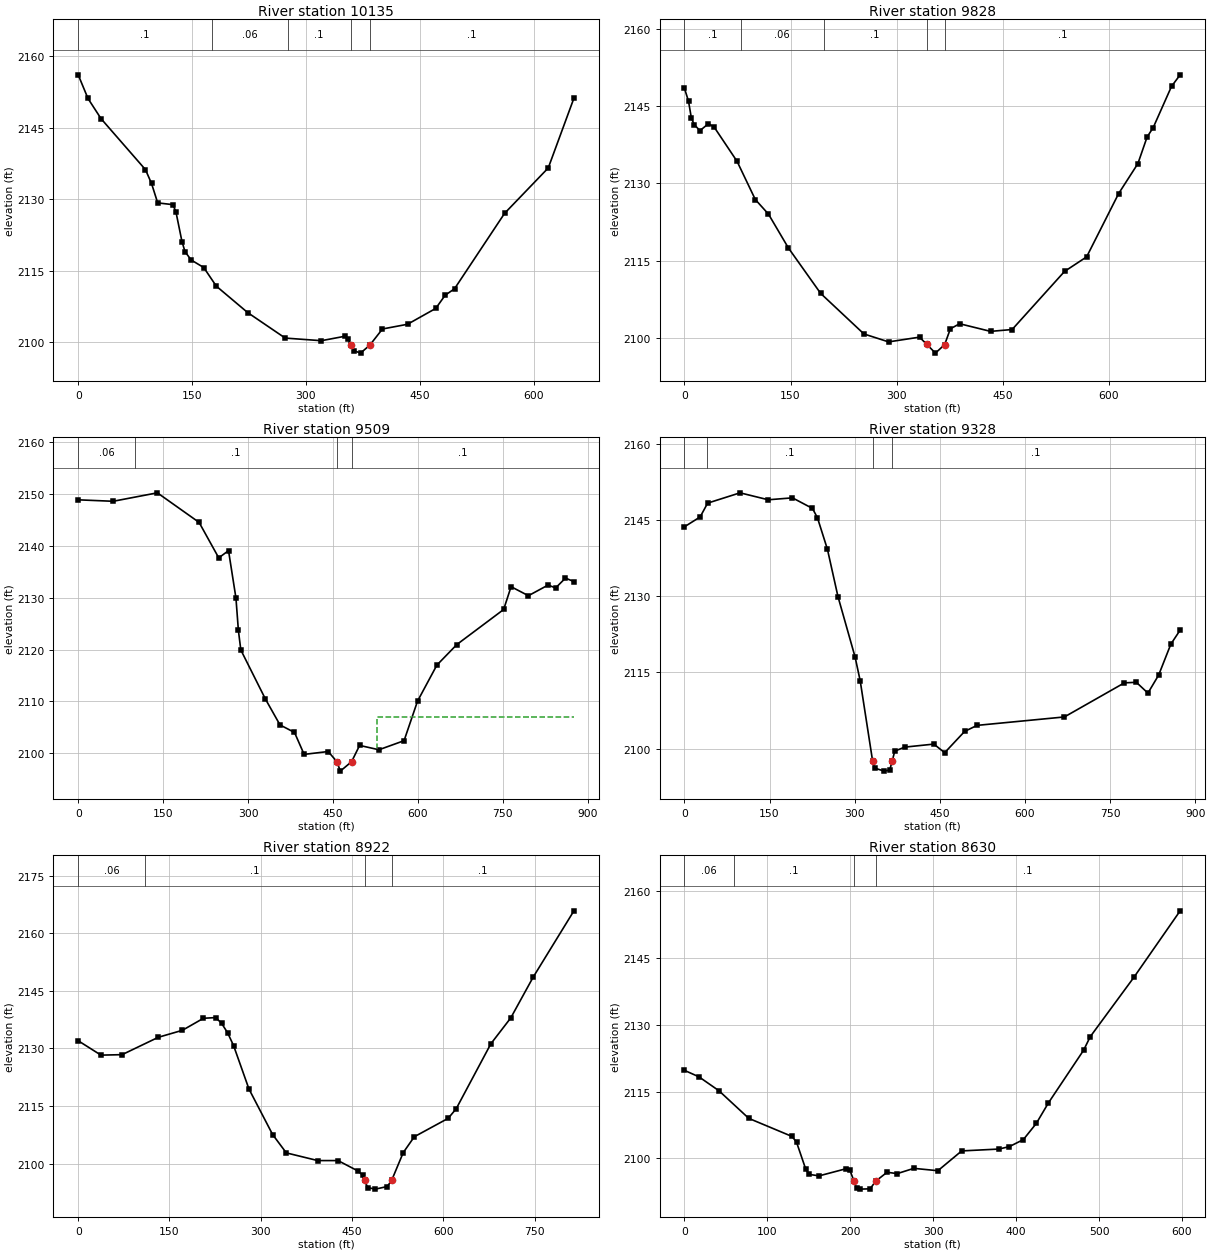
Type RM Length L Ch R = 1 ,10135   ,303.7,307.4,298.8
XS GIS Cut Line= 4
2217287.74966984664320.7770909652217433.28806942664330.588668465
2217796.31643691664237.3786822182217925.02465209664206.562328336
#Sta/Elev= 30
       0 2156.14    12.9 2151.17    30.1 2146.93    88.6 2136.23    96.6 2133.32
   104.7 2129.25   124.7 2128.88   128.7  2127.4   136.7 2121.12   140.7 2119.01
   148.8 2117.26   165.4 2115.67   181.9 2111.77   223.2 2106.22   272.7 2100.86
   320.3 2100.31   351.2 2101.24   355.3 2100.75   359.1 2099.36   363.6  2098.2
   371.9  2097.7   384.2 2099.39   400.8 2102.77   433.8 2103.76     471 2107.09
   483.4 2109.86   495.7 2111.21   561.7 2127.06   619.2 2136.59     653 2151.24
#Mann= 5 ,-1,0
       0      .1       0  175.87     .06       0  275.87      .1       0
   359.1    .045       0   384.2      .1       0
Bank Sta=359.1,384.2
XS Rating Curve= 0 ,0
Exp/Cntr=0.3,0.1

Type RM Length L Ch R = 1 ,9828    ,314.3,319.1,314.1
XS GIS Cut Line= 4
2217370.45920445664517.4471536222217545.59586282664540.994939622
2217869.37792032664399.7082236262218027.45274488664335.255423876
#Sta/Elev= 30
       0 2148.42     5.8 2145.89     9.8 2142.64    13.8 2141.38    21.9 2140.19
      34 2141.55    42.1 2140.87    74.4 2134.24   100.2 2126.83   118.8    2124
     147 2117.43   192.6 2108.62   253.7 2100.76   288.6 2099.22   332.3 2100.14
   342.6 2098.73   354.8 2097.04   367.9 2098.71   375.9 2101.76     389 2102.74
   432.7 2101.26   463.2 2101.62   537.3 2112.89   568.5 2115.71   613.8    2128
     641 2133.81     654 2138.97   662.6 2140.78   688.5 2148.78   700.7 2151.02
#Mann= 5 ,-1,0
       0      .1       0      80     .06       0  196.71      .1       0
   342.6    .045       0   367.9      .1       0
Bank Sta=342.6,367.9
XS Rating Curve= 0 ,0
Exp/Cntr=0.3,0.1

Type RM Length L Ch R = 1 ,9509    ,168.8,180.6,192.3
XS GIS Cut Line= 4
2217399.25337015 664589.482368682217716.83058603 664722.52147263
2217988.27327393664622.742144668     2218209.841      664720.079
#Sta/Elev= 30
       0 2148.88    61.7  2148.6   139.8 2150.23   213.5 2144.53   248.2 2137.69
   265.5 2139.08   278.6 2129.93   282.9  2123.7   287.2 2119.93   330.6 2110.47
   356.4 2105.47     382 2104.02     399 2099.79   441.5 2100.34     457 2098.37
   462.9 2096.56  482.84 2098.38     497 2101.52   531.1 2100.68   575.5 2102.43
   599.3 2110.06   633.5 2117.01   668.7 2120.97   751.4 2127.73   764.5 2132.13
   795.1 2130.39     830 2132.45   843.1 2131.88   860.6 2133.79   875.5 2133.11
#Mann= 4 ,-1,0
       0     .06       0     100      .1       0     457    .045       0
  482.84      .1       0
#XS Ineff= 2 , 0
                          527.94         2107.02
Permanent Ineff=
       F       F
Bank Sta=457,482.84
XS Rating Curve= 0 ,0
Exp/Cntr=0.3,0.1

Type RM Length L Ch R = 1 ,9328    ,370.7,406.1,425.5
XS GIS Cut Line= 3
2217423.00278407664663.8168421342218005.81048755664930.053997589
2218218.79889627665024.112036997
#Sta/Elev= 30
       0 2143.71    27.7 2145.66    40.9 2148.38      98 2150.41   147.7 2149.04
   190.4 2149.42   225.6 2147.34   234.4  2145.5     252 2139.28   270.6 2129.95
   300.8 2118.02   309.8 2113.33  331.55  2097.6   335.5 2096.14   352.1 2095.55
   361.9 2095.79   366.3 2097.62   370.7  2099.5   388.2 2100.28   439.6 2100.88
   458.6 2099.18   493.8 2103.38   515.8 2104.57   669.6 2106.23   775.3 2112.95
   796.4 2113.06   816.8 2110.93   835.7 2114.48   857.2 2120.58   873.6 2123.35
#Mann= 4 ,-1,0
       0     .06       0      40      .1       0  331.55    .045       0
   366.3      .1       0
Bank Sta=331.55,366.3
XS Rating Curve= 0 ,0
Exp/Cntr=0.3,0.1

Type RM Length L Ch R = 1 ,8922    ,287.6,292.4,290.7
XS GIS Cut Line= 4
2217373.97687504 664727.598818632217609.92314701664900.010947285
2217659.99162699665230.2244938282217696.36930417665415.112557869
#Sta/Elev= 30
       0 2132.01    37.4 2128.27    72.1 2128.39   131.6 2132.91   171.2 2134.73
   205.8 2137.86     226 2138.04   235.6 2136.55   245.5 2134.09   255.4 2130.72
   280.6 2119.45   319.5  2107.6     342 2102.83   393.6 2100.83   426.9 2100.83
   459.3 2098.16   467.4 2097.06   470.9 2095.68   475.5 2093.81   488.4  2093.4
   507.8 2094.08   515.1 2095.68   534.1  2102.9   552.3 2107.03   607.9 2111.82
   621.1  2114.3   678.1 2131.22   710.8 2137.95   747.4  2148.5   814.6 2165.82
#Mann= 4 ,-1,0
       0     .06       0     110      .1       0   470.9    .045       0
   515.1      .1       0
Bank Sta=470.9,515.1
XS Rating Curve= 0 ,0
Exp/Cntr=0.3,0.1

Type RM Length L Ch R = 1 ,8630    ,470.8,466.9,448.6
XS GIS Cut Line= 4
2217333.93788625664867.6589188722217340.57791563664991.356596864
2217411.22127363665325.4408107312217430.35384975665456.425370352
#Sta/Elev= 30
       0 2119.76    17.5 2118.31    41.6 2115.19    77.6 2108.99   129.8 2104.93
   135.2 2103.63   146.2 2097.63   150.3 2096.42   162.5  2096.1   195.2 2097.71
   199.3 2097.46   204.5 2094.89   207.5 2093.29   211.6 2093.12   223.9 2093.19
  230.59  2094.9   244.3  2096.9   256.6  2096.6   276.6 2097.78   305.6 2097.25
   334.3 2101.69   379.2 2102.11   391.7 2102.65   408.6 2104.22   424.2 2107.84
   438.9 2112.47   481.3 2124.28   489.3 2127.31   541.9 2140.62   597.7 2155.54
#Mann= 4 ,-1,0
       0     .06       0      60      .1       0   204.5    .045       0
  230.59      .1       0
Bank Sta=204.5,230.59
XS Rating Curve= 0 ,0
Exp/Cntr(USF)=0,0
Exp/Cntr=0.3,0.1

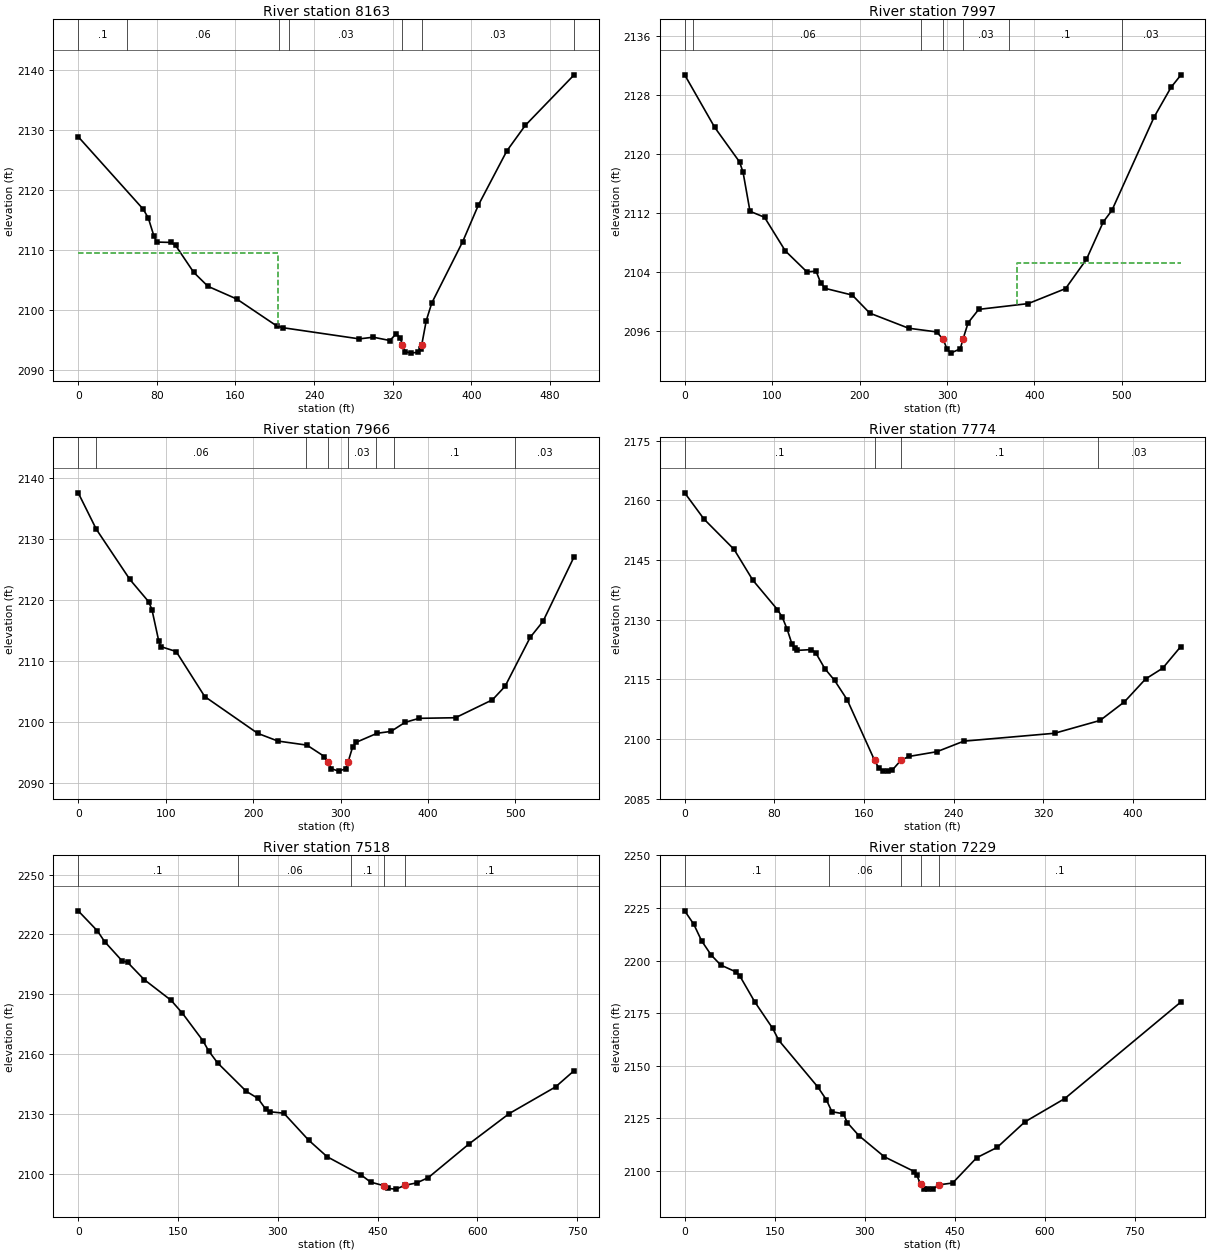
Type RM Length L Ch R = 1 ,8163    ,154,166.2,178.8
XS GIS Cut Line= 3
2216900.02498866665095.2034977682217039.53167577665181.861549753
2217262.99340143665438.710901924
#Sta/Elev= 30
       0 2128.84    66.1 2116.79    71.3 2115.33    77.1 2112.29      80 2111.31
    94.5 2111.25    99.1 2110.75   117.5 2106.28     132 2103.95   161.3 2101.84
   201.8 2097.38   207.9 2097.07   286.1  2095.2   300.3 2095.48   317.1 2094.93
   323.7 2096.05   327.7 2095.36  329.84 2094.22     333 2093.08   338.3 2092.83
   345.7 2092.98   348.5 2093.46  349.59 2094.21   354.2 2098.24   359.8 2101.17
   391.3 2111.39   407.2 2117.45   436.2 2126.48   454.9 2130.71   504.7 2139.14
#Mann= 7 ,-1,0
       0      .1       0      50     .06       0  204.23      .1       0
  214.23     .03       0  329.84    .045       0  349.59     .03       0
  504.23      .1       0
#XS Ineff= 2 , 0
          202.95 2109.57
Permanent Ineff=
       F       F
Bank Sta=329.84,349.59
XS Rating Curve= 0 ,0
Exp/Cntr(USF)=0,0
Exp/Cntr=0.3,0.1

Type RM Length L Ch R = 1 ,7997    ,30.9,30.9,30.9
XS GIS Cut Line= 4
2216884.83747032665112.538639231 2217012.4252982665210.285877435
2216991.12689251665458.4942206672217121.16268283665547.062830415
#Sta/Elev= 30
       0 2130.68    34.4 2123.56    62.8 2118.89    66.8 2117.48    74.7 2112.22
    91.3 2111.41   115.1 2106.86   139.8 2104.02   150.3 2104.12   155.4 2102.58
   160.7 2101.79   191.7 2100.88   211.7 2098.44   256.1  2096.4   288.1  2095.9
   295.72094.894   300.1 2093.55   304.1 2093.03   315.2 2093.61  318.32 2094.93
   324.2 2097.14   336.3 2098.95   392.9 2099.73   435.6 2101.76   459.5 2105.72
   478.7 2110.77   488.6 2112.34   536.9 2124.97   556.3    2129   567.2 2130.61
#Mann= 7 ,-1,0
       0      .1       0      10     .06       0  270.73     .03       0
   295.7    .045       0  318.32     .03       0  370.73      .1       0
  499.85     .03       0
#XS Ineff= 2 , 0
                          379.71         2105.19
Permanent Ineff=
       F       F
Bank Sta=295.7,318.32
XS Rating Curve= 0 ,0
Exp/Cntr(USF)=0,0
Exp/Cntr=0.3,0.1

Type RM Length L Ch R = 1 ,7966    ,217.2,191.5,162.6
XS GIS Cut Line= 4
2216853.29467356665119.0081125732216980.88250143665216.755350777
2216959.58409574665464.9636940092217089.61988606665553.532303756
#Sta/Elev= 30
       0 2137.59    20.7 2131.62    59.1 2123.39    80.6 2119.74    84.3 2118.47
      92 2113.38    94.3  2112.4     112 2111.59   144.7 2104.21   205.3 2098.18
   228.3 2096.92   261.6 2096.25   281.6 2094.38   285.42093.507   289.6 2092.39
   297.7 2091.99   305.7 2092.36  308.67 2093.51   313.7 2095.87   317.7  2096.7
   341.8 2098.19   357.7  2098.5   373.9 2099.99     390 2100.64   431.5 2100.74
   473.8 2103.68   488.2 2105.89   516.9  2113.9   531.6 2116.53   567.2 2127.13
#Mann= 8 ,-1,0
       0      .1       0      20     .06       0  260.73     .03       0
   285.4    .045       0  308.67     .03       0  340.73     .06       0
  360.73      .1       0  499.85     .03       0
Bank Sta=285.4,308.67
XS Rating Curve= 0 ,0
Exp/Cntr(USF)=0,0
Exp/Cntr=0.3,0.1

Type RM Length L Ch R = 1 ,7774    ,249.7,256.6,265.3
XS GIS Cut Line= 4
2216672.43067529665403.5342523112216773.63263068665447.761135567
  2216931.830071 665451.954792792217068.81811943665558.927948272
#Sta/Elev= 30
       0 2161.88    17.2 2155.29    44.1 2147.65    60.8 2139.92    82.7 2132.54
      87 2130.67    91.4 2127.61    95.8 2123.81    98.3 2122.82   100.1 2122.26
     113 2122.47     117 2121.63     125  2117.7   133.8  2114.7     145 2109.85
  169.39 2094.65     173  2092.8     177 2091.98     181 2091.91     185  2092.1
     193 2094.66   200.1  2095.6     225 2096.79     249 2099.44     330 2101.43
   370.6 2104.65   392.4 2109.34   411.2 2115.07   426.5 2117.79   442.5 2123.18
#Mann= 4 ,-1,0
       0      .1       0  169.39    .045       0     193      .1       0
   368.7     .03       0
Bank Sta=169.39,193
XS Rating Curve= 0 ,0
Exp/Cntr(USF)=0,0
Exp/Cntr=0.3,0.1

Type RM Length L Ch R = 1 ,7518    ,283.7,288.9,295.4
XS GIS Cut Line= 3
     2216395.674      665519.8422217008.41061486 665779.39558877
 2217081.9974461665810.465584186
#Sta/Elev= 30
       0  2231.8    28.9 2221.73    39.6 2216.41    65.7 2206.81    74.4 2205.91
      99 2197.38   139.6 2186.94   156.7 2180.43   187.3 2166.76     196 2161.62
   209.4  2155.6   252.5 2141.36   270.1  2137.8   282.1 2132.25   288.2  2131.1
     309 2130.37   346.2 2116.89   374.1 2108.55   425.6 2099.32   439.3 2095.86
   459.1 2094.05   465.4 2092.65   477.4 2092.32   491.4 2094.29   508.8 2095.45
   526.2 2098.11   587.3 2114.97   647.8  2130.2   717.3 2143.54   745.3 2151.71
#Mann= 5 ,-1,0
       0      .1       0     240     .06       0     410      .1       0
   459.1    .045       0   491.4      .1       0
Bank Sta=459.1,491.4
XS Rating Curve= 0 ,0
Exp/Cntr=0.3,0.1

Type RM Length L Ch R = 1 ,7229    ,366.3,363.9,360.3
XS GIS Cut Line= 3
      2216293.97      665631.564     2216611.967      665887.164
      2216939.39      666147.128
#Sta/Elev= 30
       0 2223.65    15.3  2217.2    28.1 2209.44    43.9 2202.72      60 2197.89
    85.2 2194.64      92 2192.62   116.5 2180.48   146.5  2167.8   156.8 2162.08
   221.8  2139.9     236 2133.83   245.2 2128.17   264.4 2127.17   270.7 2123.03
   290.2 2116.78   332.8  2106.7   382.6 2099.71   386.8 2097.95   392.9 2093.59
   398.4 2091.52   404.8 2091.36   413.4 2091.44   423.6  2093.4   446.4 2094.28
   486.4 2106.29   520.6 2111.21   566.6 2123.31     633 2134.38   826.1 2180.21
#Mann= 5 ,-1,0
       0      .1       0     240     .06       0     360      .1       0
   392.9    .045       0   423.6      .1       0
Bank Sta=392.9,423.6
XS Rating Curve= 0 ,0
Exp/Cntr=0.3,0.1