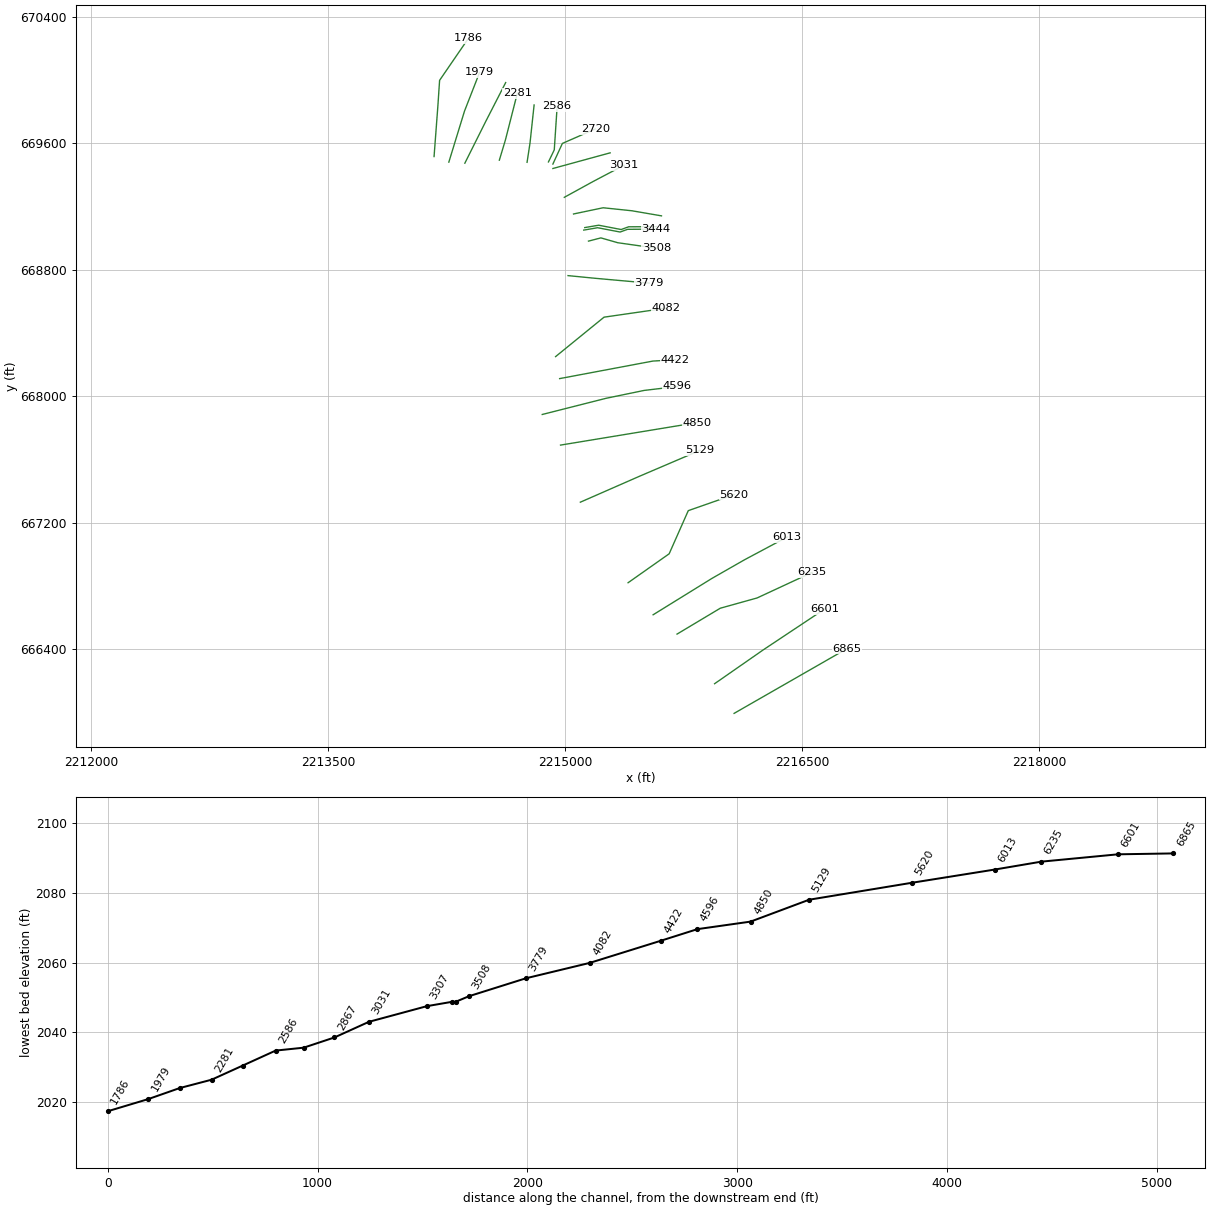
HEC-RAS study JENKSFK.prj: JENKSFK

--- JENKSFK.g01 (geometry) --- (continued)

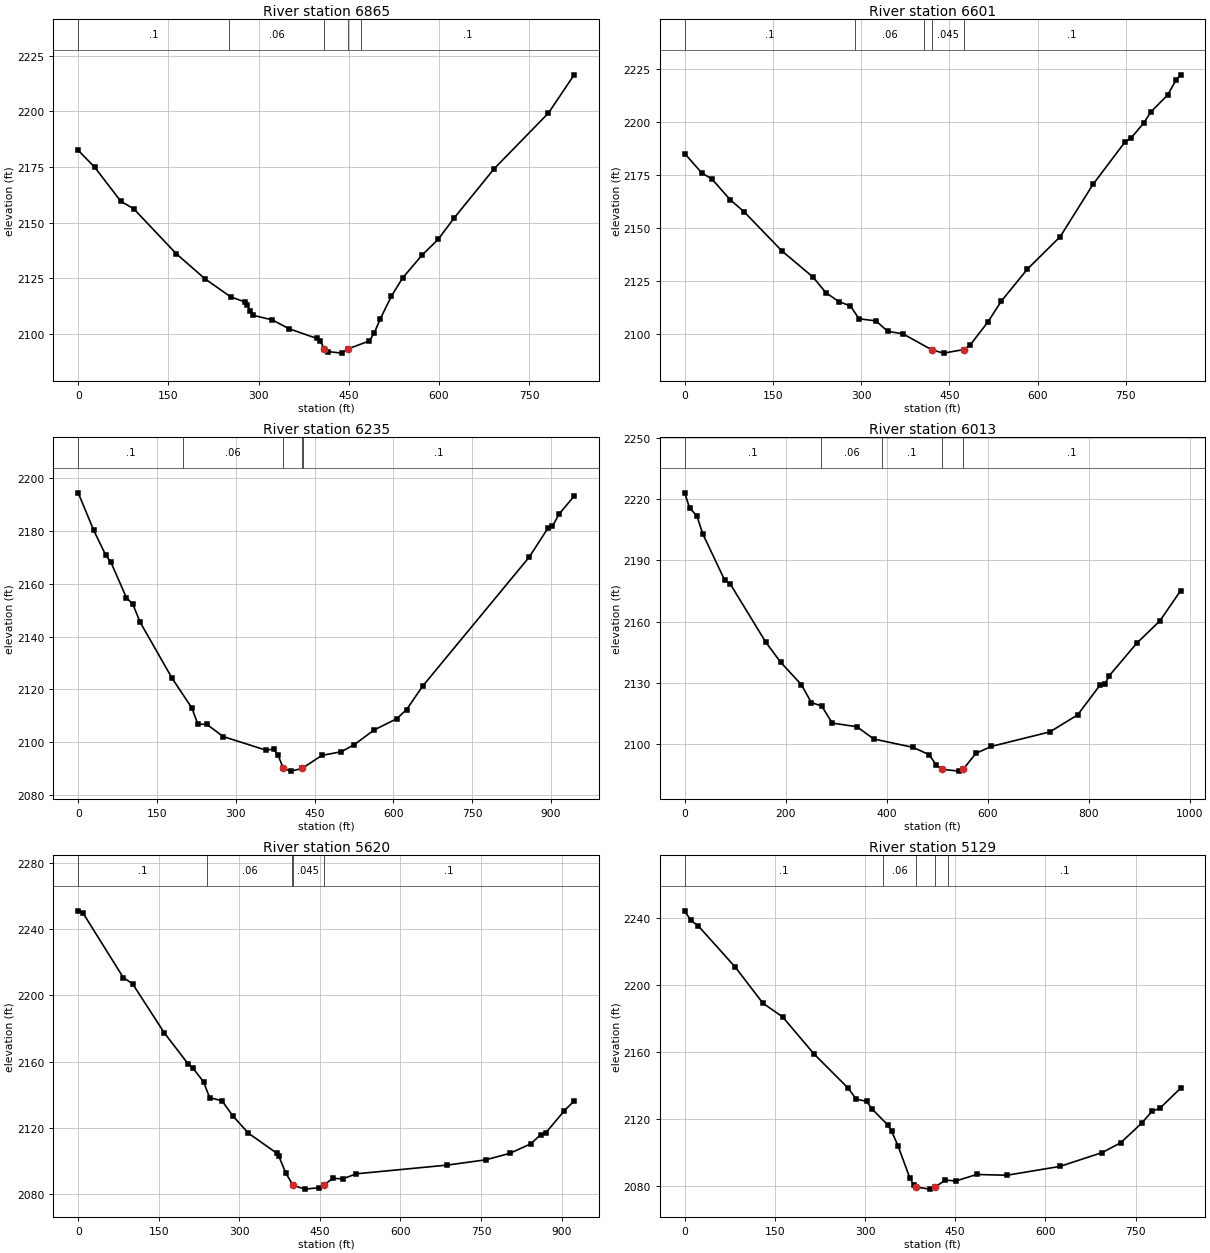
Type RM Length L Ch R = 1 ,6865    ,260.9,264.3,266.1
XS GIS Cut Line= 2
2216068.15433916665992.208049614 2216783.7450671666402.444911753
#Sta/Elev= 30
       0 2182.48    27.7 2174.78    71.1 2159.48    92.2 2156.25   162.8 2136.07
   211.1 2124.68   253.6 2116.62   276.7  2114.4   281.3 2113.05   285.9 2110.26
   290.5 2108.37   323.1 2106.24   350.4 2102.32   396.4 2097.98   402.2 2096.91
  409.51 2093.27     415 2092.05     438 2091.34   449.1 2093.29   484.3 2096.82
   492.6 2100.59   502.6 2106.87     521    2117   539.5 2125.11   571.7 2135.34
   598.6 2142.45   624.9 2151.96   691.6 2174.16   782.1 2199.24   824.8  2216.4
#Mann= 5 ,-1,0
       0      .1       0     250     .06       0  409.51    .045       0
   449.1     .06       0     470      .1       0
Bank Sta=409.51,449.1
XS Rating Curve= 0 ,0
Exp/Cntr=0.3,0.1

Type RM Length L Ch R = 1 ,6601    ,366.4,365.5,356.6
XS GIS Cut Line= 3
2215944.81923605666179.9861030922216254.37517912666395.329367833
2216642.44168745 666653.29265372
#Sta/Elev= 30
       0 2185.28    29.1  2176.1    46.4 2173.23    77.2 2163.51     101 2157.79
   164.9 2139.41   218.5 2126.88   240.2 2119.57   262.3 2115.37   281.8 2113.33
   296.4 2107.28   325.1 2106.29   345.2 2101.38   371.1 2100.18   420.1 2092.64
   440.3 2091.08   474.4 2092.76   484.9 2094.76   515.3 2105.71   538.4 2115.66
   582.7 2130.74   638.6 2146.11   694.2 2170.73   748.9 2190.86   758.7 2192.53
   780.8 2199.81   792.3 2204.84   821.2 2212.94   835.5 2220.06   843.1 2222.41
#Mann= 5 ,-1,0
       0      .1       0     290     .06       0  407.09      .1       0
   420.1    .045       0   474.4      .1       0
Bank Sta=420.1,474.4
XS Rating Curve= 0 ,0
Exp/Cntr(USF)=0,0
Exp/Cntr=0.3,0.1

Type RM Length L Ch R = 1 ,6235    ,213.2,222.1,226.2
XS GIS Cut Line= 4
2215707.04438124666494.0283641722215980.70978018666657.778971735
2216213.99831698666722.8305829592216561.68796317666884.338031514
#Sta/Elev= 30
       0 2194.51    29.4 2180.34    52.6  2170.8    61.9 2168.35    91.8 2154.74
   103.9 2152.32   117.9 2145.45   178.5 2124.29   216.5 2112.89   227.7 2106.85
   245.2 2106.66   276.3 2102.07     357 2096.96   372.3 2097.28   380.6 2094.99
  390.74    2090   405.4 2088.97   426.3 2089.99   464.1 2094.94   501.1 2096.32
     526 2099.05   563.5 2104.58   606.7 2108.84   625.3  2112.3   656.1 2121.23
     859 2170.16   894.3 2181.03   903.1 2181.82   916.3 2186.57   944.5 2193.27
#Mann= 5 ,-1,0
       0      .1       0     200     .06       0  390.74    .045       0
   426.3     .06       0  428.92      .1       0
Bank Sta=390.74,426.3
XS Rating Curve= 0 ,0
Exp/Cntr(USF)=0,0
Exp/Cntr=0.3,0.1

Type RM Length L Ch R = 1 ,6013    ,371.6,393.2,405.2
XS GIS Cut Line= 4
2215555.78631765666616.3911508922215928.62626264666846.963222136
2216134.66939014666964.7021521332216404.48777138667108.605288796
#Sta/Elev= 30
       0 2223.07     9.6 2215.75    24.1 2211.75    35.7 2203.03    79.3 2180.21
    89.8 2178.56   160.4 2149.92   189.7 2140.13   230.9 2129.05   250.8 2120.28
   271.1 2118.63     292 2110.24   340.9 2108.45   374.1 2102.46   451.7 2098.36
   483.9 2094.77   498.3 2089.49  509.39 2087.56   543.8  2086.7   551.1 2087.59
   576.1 2095.37   606.8  2098.8   722.7 2105.92   777.7 2114.26     822 2128.85
   831.5 2129.39   840.6 2133.55     895 2149.47   940.3 2160.28   981.5 2175.12
#Mann= 5 ,-1,0
       0      .1       0     270     .06       0     390      .1       0
  509.39    .045       0   551.1      .1       0
Bank Sta=509.39,551.1
XS Rating Curve= 0 ,0
Exp/Cntr(USF)=0,0
Exp/Cntr=0.3,0.1

Type RM Length L Ch R = 1 ,5620    ,511.2,490.9,467.6
XS GIS Cut Line= 4
2215397.16581474666819.1637525542215657.17261849667002.313199216
2215778.18207431667275.4021062922216067.62361056667376.788407123
#Sta/Elev= 30
       0 2251.12     8.6 2249.94      84 2210.74   101.2 2207.03   160.2  2177.4
   204.3 2158.73   213.2 2156.17   233.3 2147.82   244.7 2138.19   267.7 2136.32
   287.8 2127.22   316.8 2116.76   369.3 2104.73   373.7 2102.68   386.8 2092.46
   399.9 2085.29   421.8 2082.92     448 2083.76   456.8 2085.29   474.3 2089.42
   492.3 2089.14   518.1 2092.19   686.7 2097.43   758.7 2100.63   803.6 2104.55
   842.5 2110.27   861.4 2115.88   870.8 2117.02   905.3 2130.37   923.4 2136.24
#Mann= 5 ,-1,0
       0      .1       0     240     .06       0  398.04      .1       0
   399.9    .045       0   456.8      .1       0
Bank Sta=399.9,456.8
XS Rating Curve= 0 ,0
Exp/Cntr(USF)=0,0
Exp/Cntr=0.3,0.1

Type RM Length L Ch R = 1 ,5129    ,285.8,279.2,276.3
XS GIS Cut Line= 3
     2215095.001      667328.957     2215468.895      667492.865
     2215851.938      667656.729
#Sta/Elev= 30
       0 2244.16      10 2238.43    22.3 2235.29    84.3  2210.5   130.1 2189.03
   162.9 2180.84   215.3 2158.66   272.1 2138.26   285.2 2131.79   302.6 2130.41
   311.4 2125.93   337.6 2116.46   344.2 2112.63     355 2103.76   374.5 2084.67
   381.3 2080.37  385.56 2079.24   407.5 2078.04   416.2 2079.21   433.6 2083.42
     451 2082.92   485.8 2086.78   535.9 2086.33   624.3  2091.6   694.6  2099.9
   725.1 2105.68   759.9 2117.31   777.3 2124.49   790.3 2126.27   824.9 2138.27
#Mann= 5 ,-1,0
       0      .1       0     330     .06       0  385.56    .045       0
   416.2     .06       0  438.24      .1       0
Bank Sta=385.56,416.2
XS Rating Curve= 0 ,0
Exp/Cntr=0.3,0.1

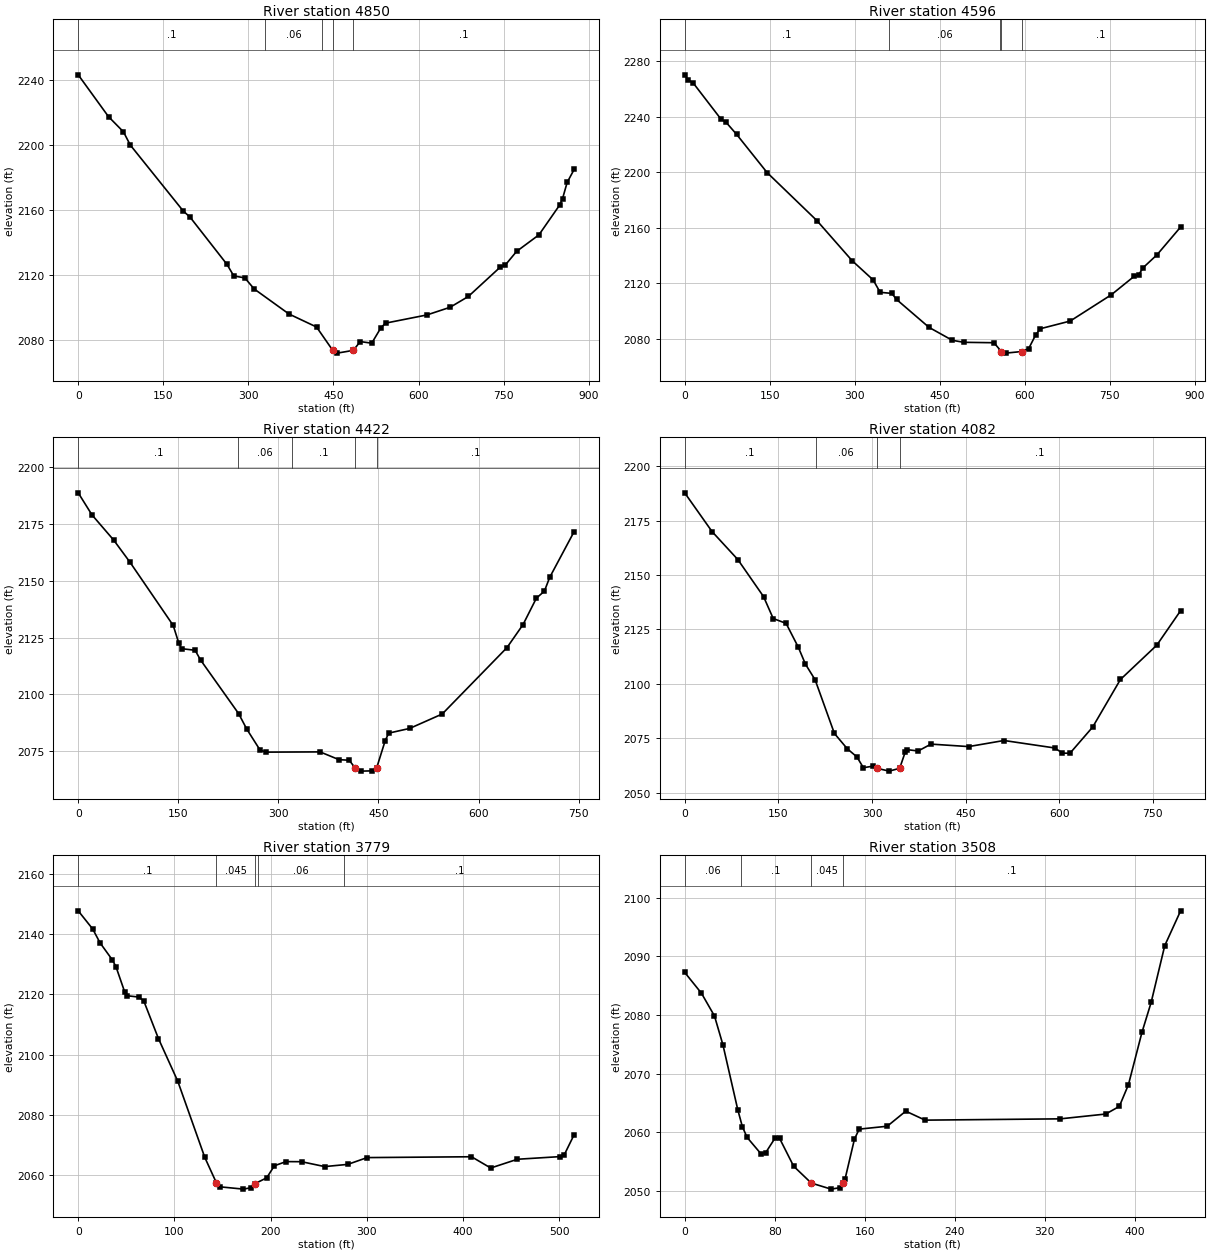
Type RM Length L Ch R = 1 ,4850    ,252.5,253.3,254.3
XS GIS Cut Line= 2
 2214969.5520713667690.303483335     2215832.333       667832.46
#Sta/Elev= 30
       0 2243.48    53.5 2217.63    79.7 2208.33    91.8 2200.15   185.1 2159.48
   197.2 2155.66   262.3 2126.51   274.3 2119.38   293.7 2118.18   310.3 2111.34
   371.6 2095.89   420.2 2087.87  448.85 2073.43   456.7 2071.75   485.1 2073.46
   497.2 2078.88   517.5 2077.89   533.7 2087.39   541.8 2090.25   614.8 2095.31
   655.6 2100.03   687.8  2106.7   744.5 2124.95   752.6 2125.94   772.9 2134.51
   812.3 2144.73   849.1 2163.24     854 2167.14   862.1 2177.12   874.4 2185.11
#Mann= 5 ,-1,0
       0      .1       0     330     .06       0     430      .1       0
  448.85    .045       0   485.1      .1       0
Bank Sta=448.85,485.1
XS Rating Curve= 0 ,0
Exp/Cntr=0.3,0.1

Type RM Length L Ch R = 1 ,4596    ,174.7,174.6,173.8
XS GIS Cut Line= 4
2214853.86179358667884.1260351242215258.18428139667986.591323131
2215499.11617482668036.4393010812215709.58541505668061.363290056
#Sta/Elev= 30
       0 2270.07     6.5 2266.22    14.8 2264.31    64.3 2238.01    72.5 2236.12
    91.7 2227.13   145.4 2199.67   233.5 2164.97   295.4 2136.21   332.5 2122.34
   344.9  2113.4   365.5 2112.62   373.8 2108.27   431.1 2088.16   472.2 2078.83
   492.7 2077.38   545.8 2077.08  558.84 2070.69   566.2 2069.59   594.8 2070.74
     607 2072.87   619.3 2082.68   627.5 2087.16   680.3 2092.71   752.8 2111.62
   793.1 2124.92   801.2 2126.19   809.2 2131.23   833.4 2140.42   875.1 2160.44
#Mann= 5 ,-1,0
       0      .1       0     360     .06       0   557.1      .1       0
  558.84    .045       0   594.8      .1       0
Bank Sta=558.84,594.8
XS Rating Curve= 0 ,0
Exp/Cntr(USF)=0,0
Exp/Cntr=0.3,0.1

Type RM Length L Ch R = 1 ,4422    ,327,339.4,348.3
XS GIS Cut Line= 3
     2214963.961      668111.1762215554.00796886668222.124519518
2215696.68472268668230.613199546
#Sta/Elev= 30
       0  2188.7    20.6 2179.01    53.3 2167.86    77.5 2158.21   142.4 2130.34
   150.8 2122.52   154.9 2120.13   175.2 2119.43   183.4 2115.14   240.4 2091.57
   252.6 2084.75   272.5 2075.54   281.1 2074.61   362.5 2074.71   390.9 2071.29
   406.2 2071.04  415.06 2067.64   423.5 2066.25   439.8 2066.36   447.3 2067.66
   460.1 2079.65   465.4 2082.97   496.8 2085.04   545.6 2091.39   642.6 2120.59
   666.7 2130.73   686.7 2142.35   698.7 2145.44   706.7 2151.53   743.3 2171.65
#Mann= 5 ,-1,0
       0      .1       0     240     .06       0     320      .1       0
  415.06    .045       0   447.3      .1       0
Bank Sta=415.06,447.3
XS Rating Curve= 0 ,0
Exp/Cntr=0.3,0.1

Type RM Length L Ch R = 1 ,4082    ,323.3,303.5,287.8
XS GIS Cut Line= 3
2214938.18134141668250.299150521 2215245.1249735668500.119215344
2215639.61846435668557.095565742
#Sta/Elev= 30
       0 2187.82    43.8 2170.02    85.1 2157.15   126.3 2140.12   141.8 2130.03
   162.4 2127.81     182 2116.83   193.4 2109.06   208.9 2101.87   239.8 2077.19
   260.4 2070.17   275.9 2066.39   286.2 2061.45     302 2062.19   307.7  2061.2
   327.5 2059.88  344.33 2061.18   353.2 2068.63     356 2069.77   373.9 2069.14
   394.5  2072.3   454.8 2071.16   511.5 2073.96   592.8 2070.52     605 2068.15
   617.1  2068.1   653.5 2080.16   697.9 2102.01   756.1 2117.77   794.3 2133.65
#Mann= 4 ,-1,0
       0      .1       0     210     .06       0   307.7    .045       0
  344.33      .1       0
Bank Sta=307.7,344.33
XS Rating Curve= 0 ,0
Exp/Cntr=0.3,0.1

Type RM Length L Ch R = 1 ,3779    ,273.4,270.5,264.6
XS GIS Cut Line= 3
2215017.18796677668763.025030026      2215183.05      668746.656
2215530.50990899668715.440602361
#Sta/Elev= 30
       0  2147.7    15.1 2141.66    22.7 2137.09    35.2 2131.56    39.2 2129.23
    48.3 2120.82    51.2 2119.55    63.3 2119.11    68.2  2117.8    83.4 2105.36
   103.5 2091.22   131.6 2065.96   143.7 2057.51   147.7 2056.22   171.8 2055.47
   179.8 2055.95   183.8  2057.3   195.9 2059.21   203.9 2063.21     216 2064.59
   232.1 2064.56   256.2 2062.94   280.2 2063.67   300.3 2065.92   408.8  2066.2
   428.8 2062.47   456.5 2065.37   501.1 2066.25   505.2 2066.83   515.5 2073.52
#Mann= 5 ,-1,0
       0      .1       0   143.7    .045       0   183.8      .1       0
  186.67     .06       0  276.67      .1       0
Bank Sta=143.7,183.8
XS Rating Curve= 0 ,0
Exp/Cntr=0.3,0.1

Type RM Length L Ch R = 1 ,3508    ,62,64.2,65.2
XS GIS Cut Line= 4
2215146.49709468668981.4329909922215224.96582776669001.856359875
2215331.91978586 668971.221306552215578.07512661668936.286596617
#Sta/Elev= 30
       0 2087.26    14.9 2083.71    26.5 2079.83      34 2074.92    47.2 2063.87
    51.3 2060.97    55.5 2059.15    67.9 2056.34      72 2056.54    80.3 2059.02
    84.4 2058.98    96.9 2054.24   112.6 2051.37   130.2 2050.34   138.5  2050.6
  140.72 2051.35   142.7 2052.14     151 2058.88   155.2 2060.56   180.1 2061.05
   196.6 2063.62   213.8 2062.09     334 2062.31   374.4 2063.13   386.5 2064.43
   394.6 2068.13   406.6 2077.03   414.8 2082.15   426.9 2091.82     441 2097.74
#Mann= 4 ,-1,0
       0     .06       0      50      .1       0   112.6    .045       0
  140.72      .1       0
Bank Sta=112.6,140.72
XS Rating Curve= 0 ,0
Exp/Cntr(USF)=0,0
Exp/Cntr=0.3,0.1

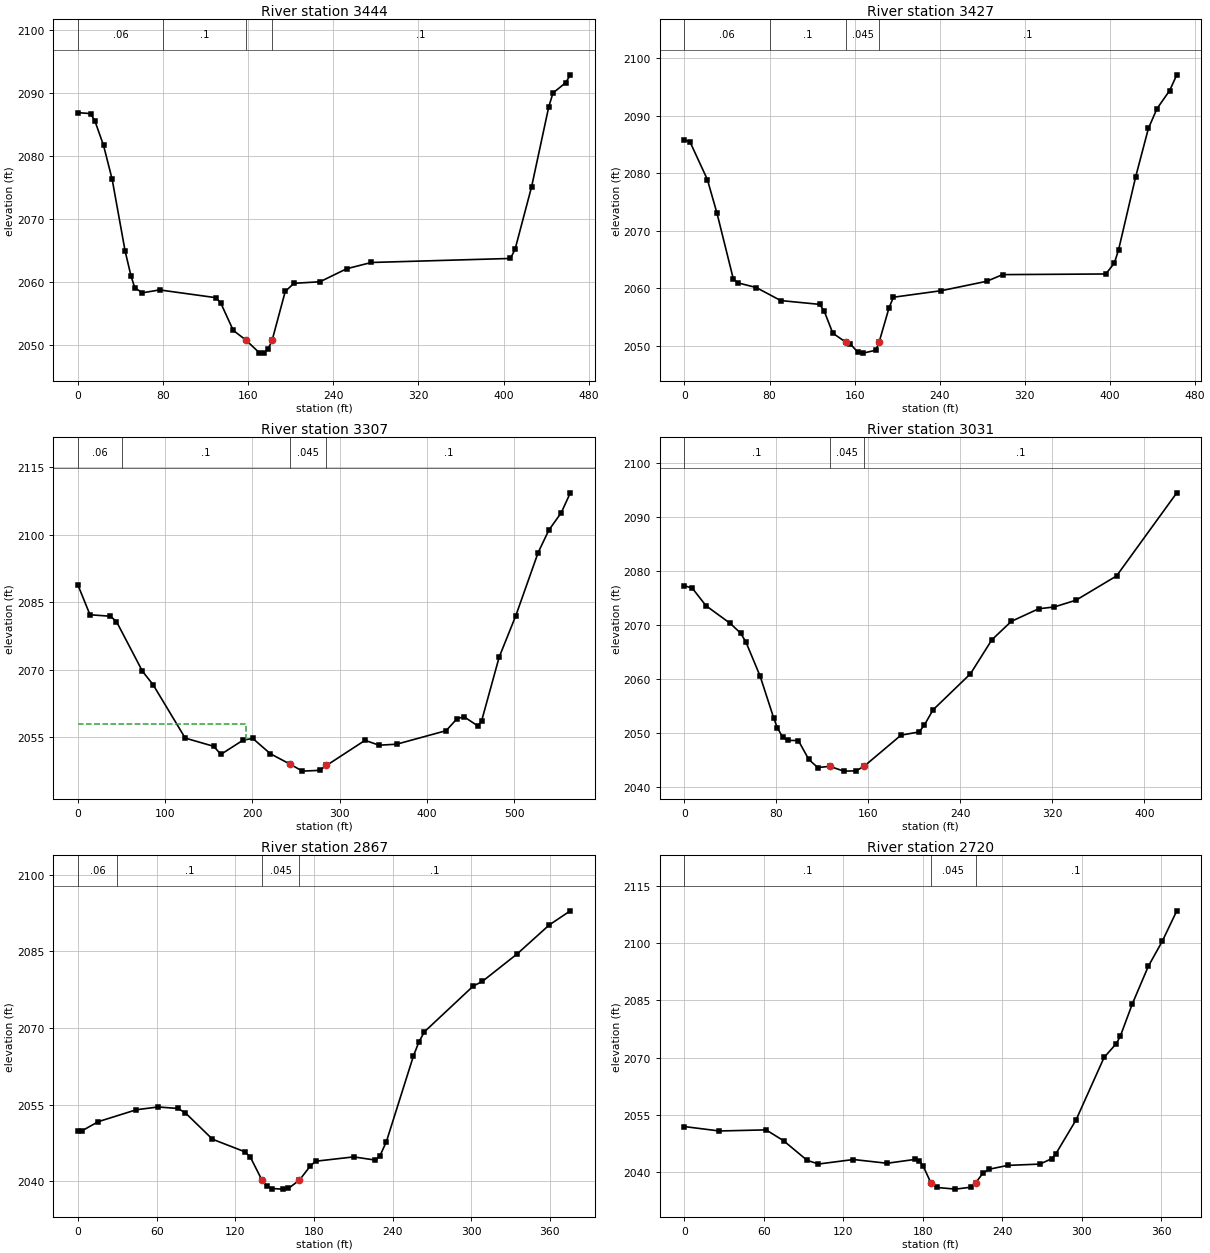
Type RM Length L Ch R = 1 ,3444    ,17.1,16.9,17.3
XS GIS Cut Line= 5
2215116.54890863669051.1591595592215204.55867104669066.216030293
2215346.58923832669038.8945181192215393.94631358669056.106348177
2215572.45100053669057.254839242
#Sta/Elev= 30
       0 2086.85    11.8 2086.69    15.9 2085.51      24 2081.64    32.1 2076.26
    44.3 2064.87    49.9 2060.88    53.4 2059.07    60.5 2058.28    76.7 2058.74
   129.6 2057.51   134.3 2056.62   145.9 2052.33   158.1 2050.75   170.4 2048.78
   174.4 2048.72   178.7 2049.35   182.5 2050.78   194.8  2058.5     203 2059.79
   227.4 2060.03   252.6  2062.1   275.7 2063.09   406.5 2063.73   410.8 2065.15
   426.4  2075.1   442.5 2087.75   446.5 2089.96   458.5  2091.6   462.8 2092.84
#Mann= 4 ,-1,0
       0     .06       0      80      .1       0   158.1    .045       0
   182.5      .1       0
Bank Sta=158.1,182.5
XS Rating Curve= 0 ,0
Exp/Cntr(USF)=0,0
Exp/Cntr=0.3,0.1

Type RM Length L Ch R = 1 ,3427    ,117.9,119.9,122.5
XS GIS Cut Line= 5
2215122.99870156669067.0717462762215211.00846397 669082.12861701
2215353.03903125669054.8071048362215400.39610651669072.018934894
2215578.90079346669073.167425959
#Sta/Elev= 30
       0 2085.78     5.3 2085.37    21.5 2078.88    30.6 2072.99    45.8 2061.68
    49.9 2060.94    67.4 2060.12    90.5 2057.85   127.1 2057.19   131.2 2056.08
   139.4 2052.19   151.6 2050.62   155.6 2050.38   162.8  2048.9   167.9 2048.72
   179.9 2049.23   183.12050.724   192.3  2056.6   196.4 2058.43   241.5 2059.57
   284.3 2061.21     299 2062.36   396.1 2062.47   404.1 2064.37   408.1  2066.7
   424.1 2079.32   436.1 2087.75   444.2  2091.2   456.1 2094.34   462.8 2097.07
#Mann= 4 ,-1,0
       0     .06       0      80      .1       0   151.6    .045       0
   183.1      .1       0
Bank Sta=151.6,183.1
XS Rating Curve= 0 ,0
Exp/Cntr(USF)=0,0
Exp/Cntr=0.3,0.1

Type RM Length L Ch R = 1 ,3307    ,260.5,276.4,298.6
XS GIS Cut Line= 4
2215051.87827075669153.2412787692215239.03901735669192.580798754
2215421.43133728669173.5070920942215608.59208388669141.320212106
#Sta/Elev= 30
       0 2088.76    13.7 2082.21    37.1 2081.88    44.1 2080.69    73.9 2069.65
    86.1 2066.66   122.9 2054.81   155.6 2052.98   163.8 2051.19   189.3 2054.36
   200.4 2054.73   220.5 2051.34   242.6 2049.07   257.3 2047.47   276.9 2047.64
   284.9 2048.73   329.1 2054.31   345.2 2053.23   365.3 2053.45   422.1 2056.46
   434.2 2059.03   442.4 2059.58   458.6 2057.49   462.7 2058.58   482.9 2072.79
     502 2082.01   527.6 2096.03   539.8 2100.99   554.1 2104.88   564.5  2109.3
#Mann= 4 ,-1,0
       0     .06       0      50      .1       0   242.6    .045       0
   284.9      .1       0
#XS Ineff= 2 , 0
          192.68 2058.03
Permanent Ineff=
       F       F
Bank Sta=242.6,284.9
XS Rating Curve= 0 ,0
Exp/Cntr(USF)=0,0
Exp/Cntr=0.3,0.1

Type RM Length L Ch R = 1 ,3031    ,168.1,164.3,158.8
XS GIS Cut Line= 3
2214993.37712256669258.5907324882215180.22196089 669361.13813213
2215370.54298226669461.078394492
#Sta/Elev= 30
       0 2077.35     6.9 2076.85    18.7 2073.63    39.7 2070.37    48.8 2068.55
    53.4 2066.91    65.8 2060.56    77.6  2052.8    80.8 2050.98    85.3 2049.29
    89.9 2048.67      99 2048.64   108.1 2045.13   115.9 2043.63   126.4 2043.86
   138.4 2042.97   149.2 2043.02  156.18 2043.87   188.3 2049.64     204 2050.23
   208.5 2051.48   216.1 2054.32   248.7 2061.02   267.3 2067.32   284.2 2070.73
   307.9 2073.06   321.5  2073.4   340.5 2074.66   375.7 2079.15   428.1 2094.56
#Mann= 3 ,-1,0
       0      .1       0   126.4    .045       0  156.18      .1       0
Bank Sta=126.4,156.18
XS Rating Curve= 0 ,0
Exp/Cntr(USF)=0,0
Exp/Cntr=0.3,0.1

Type RM Length L Ch R = 1 ,2867    ,142.9,146.9,149.5
XS GIS Cut Line= 2
2214921.24632451 669441.090342022215283.63840629669540.161558623
#Sta/Elev= 30
       0 2049.81       3  2049.9    15.5 2051.69    44.5 2054.02    61.1 2054.56
    76.2 2054.27    81.8 2053.44   102.6 2048.25   127.4 2045.78   131.6 2044.69
  140.38 2040.24     144  2039.1   148.2 2038.59   156.5 2038.48   160.6 2038.63
   168.9 2040.23   177.2 2042.98   181.3 2043.94   210.4 2044.79     227 2044.16
   230.4 2044.99   235.3 2047.76     256 2064.57   260.1 2067.26   264.3 2069.27
   301.6 2078.23   308.6 2079.15   335.1 2084.52   359.7 2090.21   375.7 2092.96
#Mann= 4 ,-1,0
       0     .06       0      30      .1       0  140.38    .045       0
   168.9      .1       0
Bank Sta=140.38,168.9
XS Rating Curve= 0 ,0
Exp/Cntr(USF)=0,0
Exp/Cntr=0.3,0.1

Type RM Length L Ch R = 1 ,2720    ,102.6,133.3,152.6
XS GIS Cut Line= 3
2214921.19803389669469.2809522652214981.42290503669599.898529944
2215190.25460108669691.409048438
#Sta/Elev= 30
       0 2051.93    26.3 2050.78    61.6 2051.07    74.8 2048.23    92.6 2043.09
   101.2 2042.12   127.6  2043.3     153 2042.32   174.2 2043.33   177.4 2042.98
   180.3 2041.54   186.1 2037.18   190.5 2035.98   204.6 2035.54   216.7 2036.06
   219.8 2037.17   225.4 2039.71   229.8 2040.73   244.1 2041.76   268.4  2042.1
   277.5 2043.54   280.5 2044.82   295.7 2053.66   316.9 2070.06   326.1 2073.67
   329.1 2075.58   338.2 2084.07   350.3 2093.95   360.8 2100.48   371.8 2108.48
#Mann= 3 ,-1,0
       0      .1       0   186.1    .045       0   219.8      .1       0
Bank Sta=186.1,219.8
XS Rating Curve= 0 ,0
Exp/Cntr(USF)=0,0
Exp/Cntr=0.3,0.1

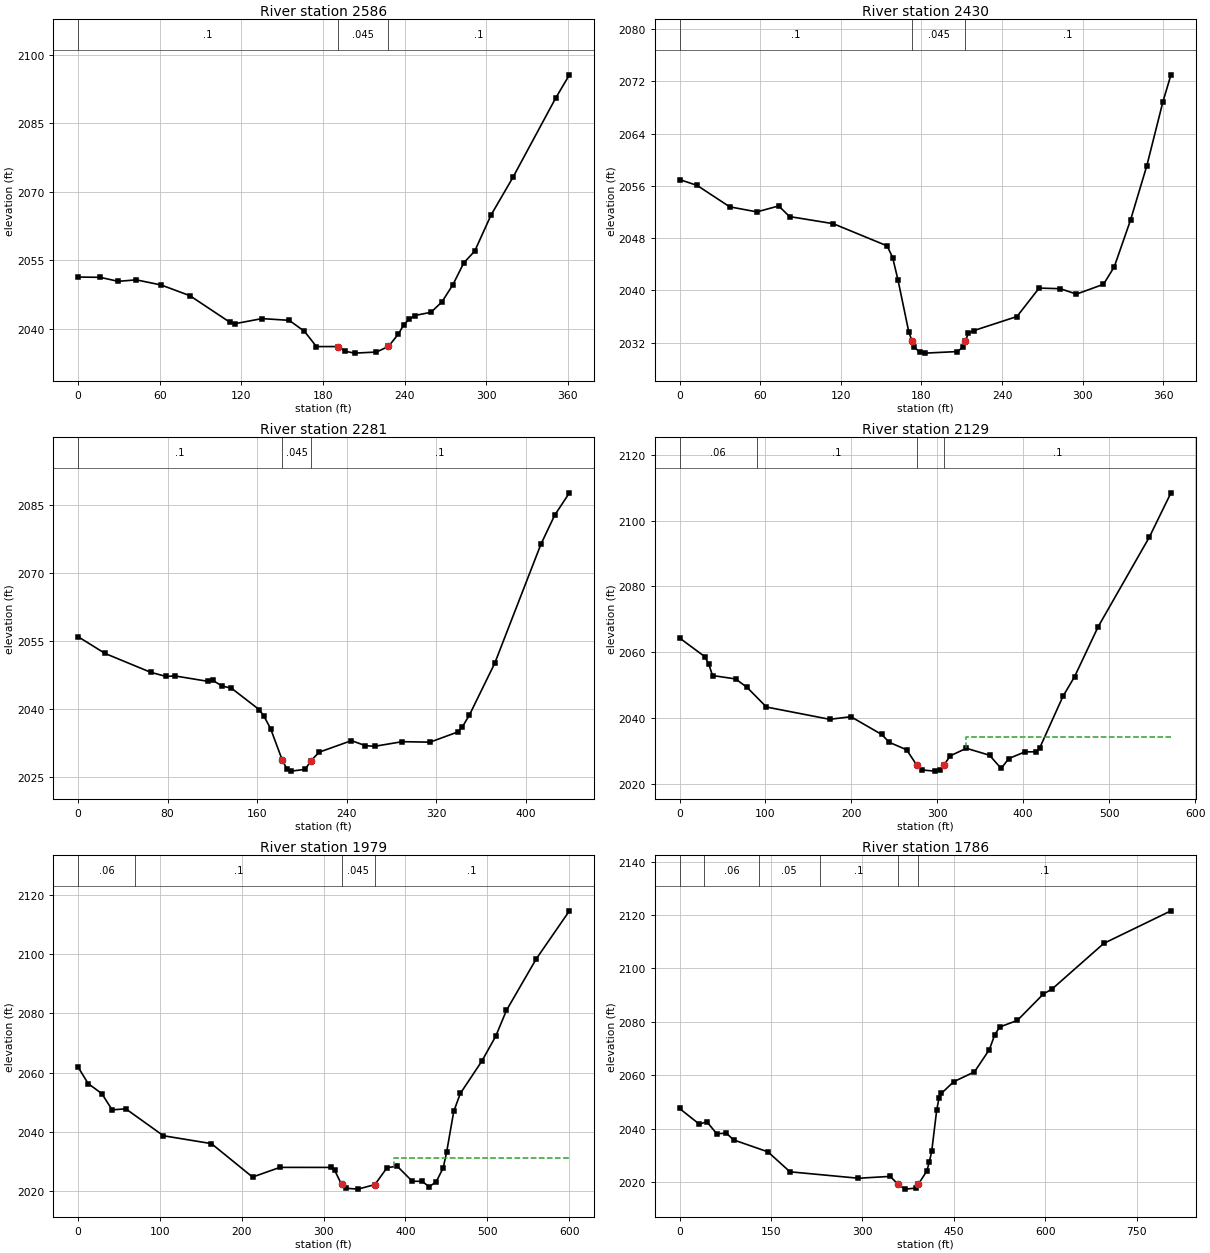
Type RM Length L Ch R = 1 ,2586    ,157.5,156.7,155.3
XS GIS Cut Line= 3
2214893.04095127669482.5773523882214929.92605315669558.937238616
2214948.16528514669834.671510512
#Sta/Elev= 30
       0 2051.36    16.2 2051.31    29.5 2050.43    42.9 2050.75    61.2 2049.62
    82.2 2047.29   111.6 2041.47   115.3 2041.15   135.2 2042.27   155.2 2041.89
   166.4 2039.48   175.2 2036.14   191.3 2036.15   196.4 2035.11   203.3 2034.71
   219.3 2034.95   228.1 2036.17   235.4 2038.88   239.4 2040.94   243.4 2042.15
   247.4 2042.94   259.4 2043.65   267.4 2045.92   275.5  2049.7   283.5 2054.49
   291.5 2057.04   303.5 2064.94   319.6  2073.2   350.9  2090.5   361.1 2095.64
#Mann= 3 ,-1,0
       0      .1       0   191.3    .045       0   228.1      .1       0
Bank Sta=191.3,228.1
XS Rating Curve= 0 ,0
Exp/Cntr(USF)=0,0
Exp/Cntr=0.3,0.1

Type RM Length L Ch R = 1 ,2430    ,151,148.8,146.4
XS GIS Cut Line= 3
2214757.73052649669480.230928837 2214776.5019149669603.027094679
2214802.31257396669843.144438077
#Sta/Elev= 30
       0 2056.97    13.1 2056.07    37.4 2052.79    57.6 2052.02    73.8 2052.93
    81.9  2051.3   114.3 2050.22   154.5 2046.82   158.6 2045.03   162.6 2041.58
   170.6 2033.67   173.1 2032.21   174.7 2031.34   178.7 2030.54   182.7 2030.41
   206.8 2030.65   210.9 2031.33   212.7 2032.26   214.9 2033.44   218.9 2033.85
   251.1 2036.01   267.6 2040.36   283.3 2040.27   295.4 2039.44   315.5 2040.94
   323.5 2043.61   335.6 2050.76   347.7 2059.05   359.7 2068.86   365.7 2072.99
#Mann= 3 ,-1,0
       0      .1       0   173.1    .045       0   212.7      .1       0
Bank Sta=173.1,212.7
XS Rating Curve= 0 ,0
Exp/Cntr(USF)=0,0
Exp/Cntr=0.3,0.1

Type RM Length L Ch R = 1 ,2281    ,156.4,152,148.1
XS GIS Cut Line= 3
2214582.28949974669493.9650705282214620.91375573 669622.39072168
 2214696.2310549669917.866279969
#Sta/Elev= 30
       0 2055.97    24.2 2052.26    65.1  2048.1    78.5 2047.21    86.9  2047.3
   116.1 2046.12   120.3 2046.35   128.7 2045.08     137 2044.63   161.8  2039.9
   165.9 2038.54     172 2035.73   182.4 2028.82   186.5 2026.87   190.6 2026.34
     203 2026.74   208.2 2028.65   215.4 2030.51   244.3 2033.06   256.7 2031.95
     265 2031.81   289.7 2032.83   314.5 2032.72   339.3 2034.97   343.4 2036.11
   349.6 2038.67   372.3 2050.12   413.6 2076.37   425.9 2082.75     439 2087.65
#Mann= 3 ,-1,0
       0      .1       0   182.4    .045       0   208.2      .1       0
Bank Sta=182.4,208.2
XS Rating Curve= 0 ,0
Exp/Cntr(USF)=0,0
Exp/Cntr=0.3,0.1

Type RM Length L Ch R = 1 ,2129    ,146.3,150,153
XS GIS Cut Line= 3
 2214363.9486092669474.813369676     2214496.625      669739.868
2214622.32015002669985.015399664
#Sta/Elev= 30
       0 2064.37    29.5 2058.67      34 2056.47    38.4 2052.96    65.3 2051.92
    78.7 2049.34   101.1  2043.4   174.8 2039.67   199.5 2040.45   235.2 2035.08
   244.2 2032.67   264.3 2030.42   276.2 2025.71   282.1  2024.3     297 2023.94
     303 2024.28  307.57 2025.69   314.9 2028.56   333.8 2030.88   360.8 2028.76
   374.3 2024.75   383.2 2027.77   401.9 2029.77   414.8 2029.82   419.2    2031
   446.2 2046.63   459.7 2052.59   487.2 2067.78   546.7 2094.95   571.9 2108.42
#Mann= 4 ,-1,0
       0     .06       0      90      .1       0   276.2    .045       0
  307.57      .1       0
#XS Ineff= 2 , 0
                          333.63         2034.45
Permanent Ineff=
       F       F
Bank Sta=276.2,307.57
XS Rating Curve= 0 ,0
Exp/Cntr=0.3,0.1

Type RM Length L Ch R = 1 ,1979    ,185.5,192.5,196.4
XS GIS Cut Line= 3
2214262.56230837669481.354421343     2214361.814      669804.569
2214457.15859545670048.790653413
#Sta/Elev= 30
       0 2061.96    12.4 2056.36    29.1 2052.96    41.7 2047.49    58.4 2047.83
   104.4 2038.76     163 2036.11   213.2 2024.84   246.7  2028.1   308.5 2028.09
   313.6 2027.07     322 2022.33   327.7 2021.06   342.1 2020.77  362.72 2022.31
   377.4 2027.96   389.8 2028.53   408.3 2023.43   420.4 2023.39   428.9 2021.57
   437.5 2023.22   446.1 2027.92   450.4 2033.41     459 2046.98     467 2053.01
   493.3 2063.92   510.3 2072.33   523.4 2081.04   559.7 2098.35   600.3 2114.58
#Mann= 4 ,-1,0
       0     .06       0      70      .1       0     322    .045       0
  362.72      .1       0
#XS Ineff= 2 , 0
                          386.48         2031.18
Permanent Ineff=
       F       F
Bank Sta=322,362.72
XS Rating Curve= 0 ,0
Exp/Cntr=0.3,0.1

Type RM Length L Ch R = 1 ,1786    ,171.8,176.5,179.7
XS GIS Cut Line= 4
2214169.04701119669516.5387775792214193.49229759669840.814732364
2214204.11396798669999.174181905     2214386.529      670264.962
#Sta/Elev= 30
       0 2047.51    32.7 2041.59    44.8 2042.56    60.8  2038.1    76.9 2038.21
    88.9 2035.72   145.1 2031.25   181.2 2023.78   293.5 2021.37   345.6 2022.06
   358.1 2019.22   369.4 2017.29   387.2 2017.65  392.04 2019.19   405.7 2024.07
   409.7 2027.32   413.8  2031.5     422 2046.95   425.7 2051.31   429.5 2053.12
   449.8 2057.52   483.9 2061.21   508.4 2069.58     517    2075   525.2 2078.01
   554.3 2080.49   597.1 2090.41   611.3 2092.25   696.1 2109.34   806.3 2121.54
#Mann= 6 ,-1,0
       0      .1       0      40     .06       0     130     .05       0
     230      .1       0   358.1    .045       0  392.04      .1       0
Bank Sta=358.1,392.04
XS Rating Curve= 0 ,0
Exp/Cntr=0.3,0.1