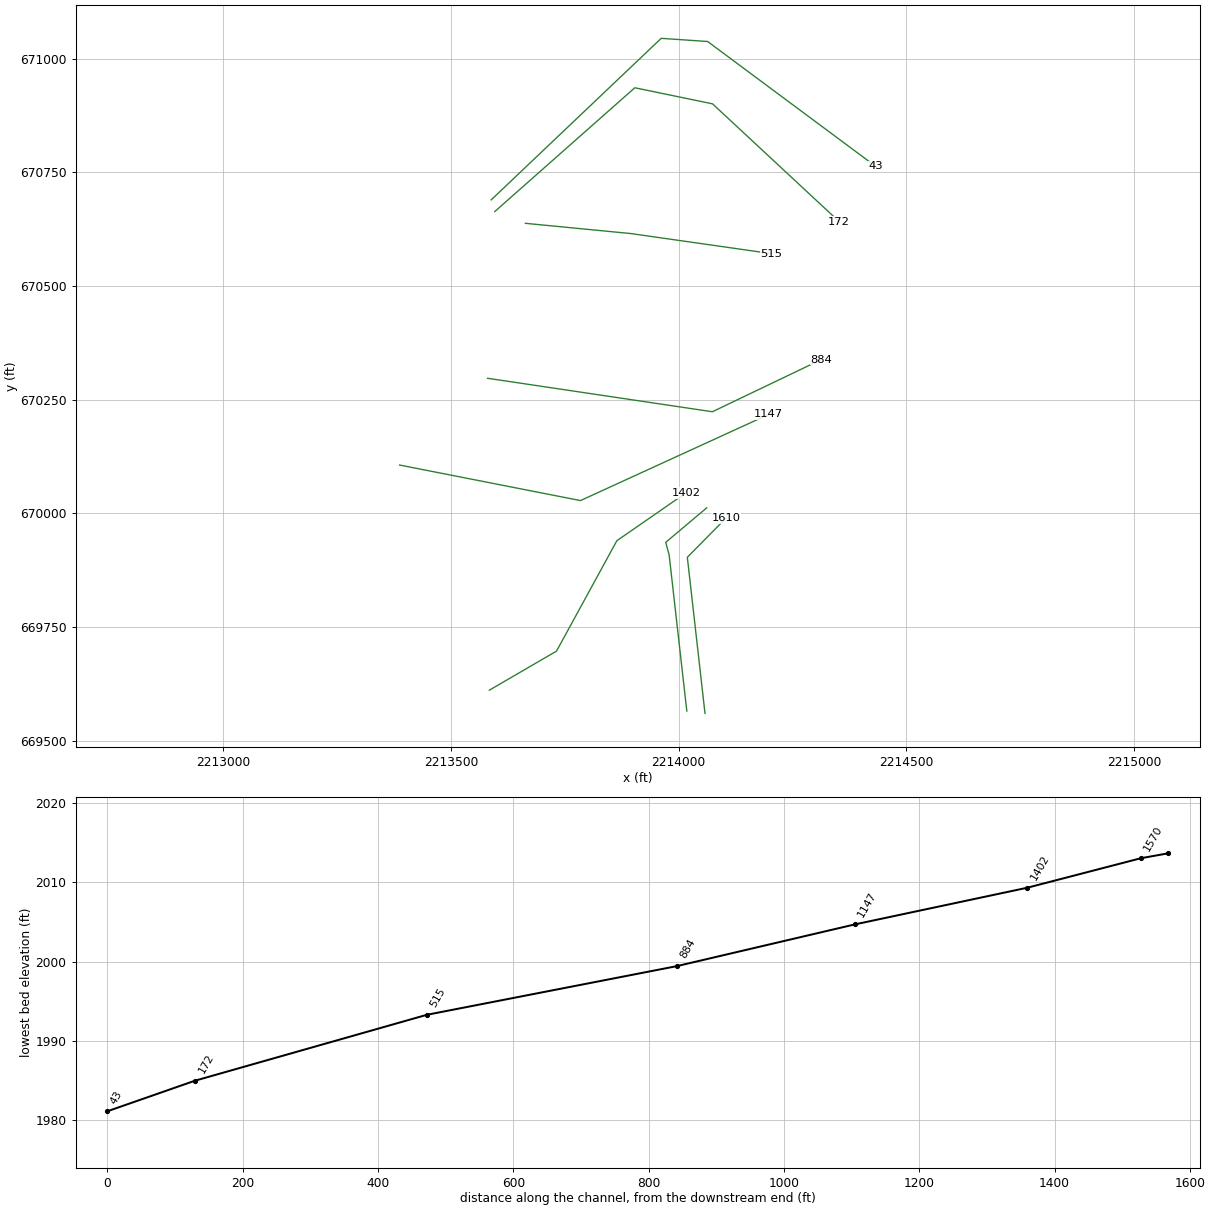
HEC-RAS study JENKSFK.prj: JENKSFK

--- JENKSFK.g01 (geometry) --- (continued)

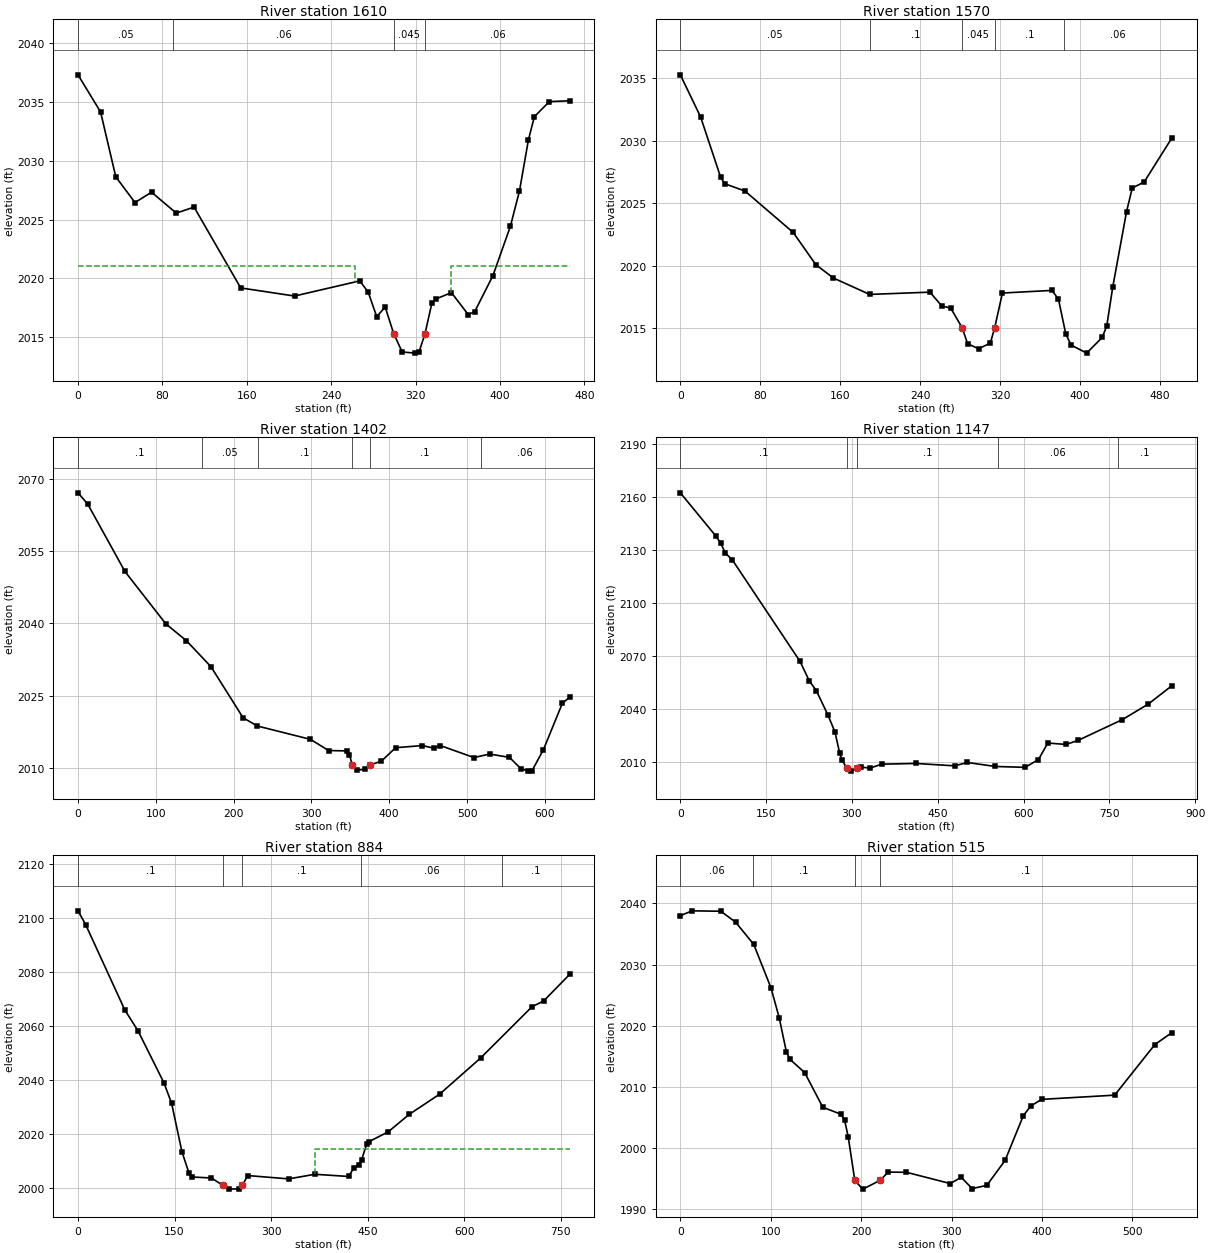
Type RM Length L Ch R = 1 ,1610    ,39.9,39.8,39.4
XS GIS Cut Line= 3
2214057.85261143669559.9130442432214019.03760471669903.225529306
2214103.64536984669989.065463699
#Sta/Elev= 30
       0 2037.33    21.4 2034.17    35.8 2028.65      54 2026.46    69.7 2027.34
    93.1 2025.56     110 2026.07   154.2 2019.19   205.2  2018.5     267 2019.79
     275 2018.84   283.1 2016.74   291.1 2017.57  299.15 2015.31   307.2 2013.74
   319.3 2013.64   323.3 2013.76  328.86  2015.3   335.4 2017.91   339.4 2018.26
   353.9 2018.79   369.9 2016.91     376 2017.18   393.2 2020.23   409.8 2024.44
   418.4 2027.45   426.9 2031.81   432.5 2033.77   446.7 2035.05     466 2035.12
#Mann= 4 ,-1,0
       0     .05       0      90     .06       0  299.15    .045       0
  328.86     .06       0
#XS Ineff= 2 , 0
          262.61 2021.05  353.63         2021.09
Permanent Ineff=
       F       F
Bank Sta=299.15,328.86
XS Rating Curve= 0 ,0
Exp/Cntr(USF)=0,0
Exp/Cntr=0.3,0.1

Type RM Length L Ch R = 1 ,1570    ,176.6,168.1,155.3
XS GIS Cut Line= 4
2214017.90545926669565.0271824062213979.09045254 669908.33966747
2213971.54088194669936.0666622542214061.54838936670011.915685366
#Sta/Elev= 30
       0 2035.26    20.3 2031.89    40.4 2027.06    44.4 2026.56    64.6 2025.98
   112.9 2022.67   135.5  2020.1   153.1 2019.03   189.4 2017.72   249.7  2017.9
   261.4 2016.81   270.5 2016.62   281.9 2015.06   287.4 2013.78   298.3 2013.38
   310.1 2013.83  314.52 2015.07   322.2 2017.83   371.8 2018.04   378.3 2017.33
   385.5 2014.59   390.8 2013.68   406.5 2013.03   422.1 2014.29   426.6 2015.21
   432.6 2018.32   446.4 2024.34   452.1 2026.22     464  2026.7   491.9 2030.24
#Mann= 5 ,-1,0
       0     .05       0     190      .1       0   281.9    .045       0
  314.52      .1       0  384.24     .06       0
Bank Sta=281.9,314.52
XS Rating Curve= 0 ,0
Exp/Cntr(USF)=0,0
Exp/Cntr=0.3,0.1

Type RM Length L Ch R = 1 ,1402    ,270.5,254.9,234.3
XS GIS Cut Line= 4
2213584.03694752669610.9103659362213731.68971251 669696.87259213
2213864.17267288669939.589466088 2214015.8707191670044.766778136
#Sta/Elev= 30
       0 2067.14    12.5  2064.8    60.3  2050.8   112.9 2039.91   139.3 2036.42
   170.9 2031.01   212.2  2020.4   230.4 2018.69   298.8 2015.91   322.1 2013.59
   345.4 2013.51   348.9 2012.71  352.51 2010.58     358  2009.5     369  2009.7
   374.8 2010.58   389.9 2011.37   408.2 2014.18   442.7 2014.62   457.1 2014.09
   465.8 2014.62   508.9 2012.13     529 2012.86   554.5 2012.17   569.2 2009.84
   578.8 2009.31   583.7 2009.44   598.3  2013.8   622.6 2023.43     632 2024.67
#Mann= 6 ,-1,0
       0      .1       0     160     .05       0  230.85      .1       0
  352.51    .045       0   374.8      .1       0  517.37     .06       0
Bank Sta=352.51,374.8
XS Rating Curve= 0 ,0
Exp/Cntr(USF)=0,0
Exp/Cntr=0.3,0.1

Type RM Length L Ch R = 1 ,1147    ,257.1,262.8,265.4
XS GIS Cut Line= 3
2213386.94824345670106.1022296752213784.31713219 670027.95301489
2214197.58077648670217.365518523
#Sta/Elev= 30
       0 2162.51    62.4 2137.89    70.6 2133.92    78.7 2128.33    90.9 2124.47
   209.2 2066.94   225.5 2055.83   237.7 2050.38   258.1 2036.44   270.3 2026.87
   278.5 2014.97   282.5 2011.03  291.27 2006.26   298.8 2004.69   308.4 2006.28
   315.2 2007.03   331.5 2006.39   351.8 2008.62   411.8 2009.04   479.6 2007.69
   501.6  2009.6   550.6 2007.33   602.8 2006.83   626.1 2011.27   642.4 2020.62
   674.3 2019.82   695.2  2022.1   772.7  2033.9   818.4 2042.79   859.6 2053.22
#Mann= 5 ,-1,0
       0      .1       0  291.27    .045       0   308.4      .1       0
  554.98     .06       0  764.98      .1       0
Bank Sta=291.27,308.4
XS Rating Curve= 0 ,0
Exp/Cntr(USF)=0,0
Exp/Cntr=0.3,0.1

Type RM Length L Ch R = 1 ,884     ,367,369.4,368.9
XS GIS Cut Line= 3
 2213580.2363202670296.9210594172214074.08572102670223.334228168
2214312.83410684670337.802632332
#Sta/Elev= 30
       0 2102.78    12.1 2097.56    72.7 2065.99      93 2058.33   133.5 2038.94
   145.5 2031.27   161.6 2013.24   172.2 2005.58   177.9 2003.93   207.4 2003.58
     225 2000.84   234.5 1999.44   250.7 1999.53  255.62 2000.87   263.7 2004.48
   327.5 2003.24     368 2004.95   420.5 2004.14   428.6 2007.33   436.7 2008.57
   440.8 2010.41   448.8 2016.32   451.7 2017.02   481.9 2020.69   514.9 2027.23
   562.2 2034.75   625.8 2048.16   705.7 2067.21   723.4 2069.26   764.1  2079.2
#Mann= 5 ,-1,0
       0      .1       0     225    .045       0  255.62      .1       0
     440     .06       0   659.3      .1       0
#XS Ineff= 2 , 0
                          368.28         2014.34
Permanent Ineff=
       F       F
Bank Sta=225,255.62
XS Rating Curve= 0 ,0
Exp/Cntr(USF)=0,0
Exp/Cntr=0.3,0.1

Type RM Length L Ch R = 1 ,515     ,337.8,343.1,336.6
XS GIS Cut Line= 3
2213663.35203633670637.7571257212213895.09757224670615.226309729
2214203.01872412670571.237573746
#Sta/Elev= 30
       0 2037.97    12.9 2038.77    44.8  2038.7    61.1 2036.92    81.2 2033.29
   100.2 2026.21   109.3 2021.34   117.4 2015.66   121.4 2014.49   137.5 2012.35
   157.6 2006.68   177.7 2005.54   181.7 2004.57   185.7 2001.85  192.98 1994.73
   201.8 1993.31     221 1994.74   229.9 1996.09   250.1 1996.06   298.6 1994.22
   310.7 1995.24   322.8  1993.4     339 1993.92   359.2    1998   379.4 2005.31
   387.5 2006.88   399.6 2007.97   480.4 2008.66   524.9 2016.93   543.9 2018.89
#Mann= 4 ,-1,0
       0     .06       0      80      .1       0  192.98    .045       0
     221      .1       0
Bank Sta=192.98,221
XS Rating Curve= 0 ,0
Exp/Cntr(USF)=0,0
Exp/Cntr=0.3,0.1

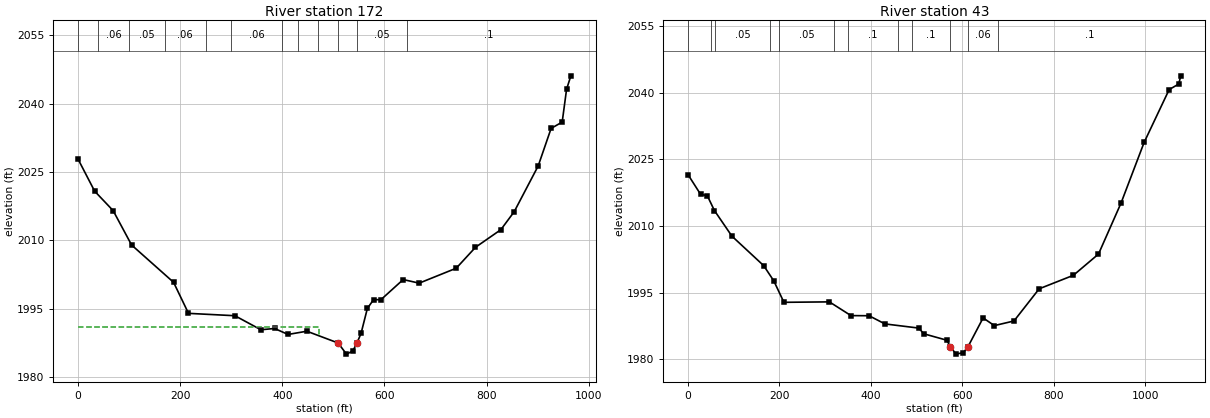
Type RM Length L Ch R = 1 ,172     ,125.6,129.1,131.6
XS GIS Cut Line= 4
 2213596.0411475670663.6405674872213903.63410212670935.911843105
2214074.35555061670900.5901641062214352.51377273670641.564518112
#Sta/Elev= 30
       0  2027.8    32.5 2020.77    68.7  2016.5   104.9 2008.95   187.1 2000.76
   216.3 1993.95   307.2 1993.43   358.1 1990.35   384.8 1990.63   411.3 1989.32
   448.1 1990.03   509.4 1987.44   525.7    1985     538 1985.68   546.1  1987.4
   554.3 1989.57   566.6 1995.02   578.8 1996.97   593.1 1996.94   636.8 2001.37
   668.1 2000.58   740.7 2003.86   778.4 2008.45   828.1 2012.32   854.3 2016.28
   901.2 2026.31   926.5 2034.55   948.2 2035.94   956.8 2043.14   965.2 2046.09
#Mann= 12 ,-1,0
       0     .07       0      40     .06       0     100     .05       0
     170     .06       0     250     .05       0     300     .06       0
     400      .1       0  430.79     .07       0  470.79     .06       0
   509.4    .045       0   546.1     .05       0  645.12      .1       0
#XS Ineff= 2 , 0
           472.6 1991.03
Permanent Ineff=
       F       F
Bank Sta=509.4,546.1
XS Rating Curve= 0 ,0
Exp/Cntr(USF)=0,0
Exp/Cntr=0.3,0.1

Type RM Length L Ch R = 1 ,43      ,,,
XS GIS Cut Line= 4
2213588.16664629670689.3264248572213961.64798178 671044.62040121
2214063.64701355671037.6515232632214432.58578624670763.215577196
#Sta/Elev= 30
       0 2021.57    27.6 2017.12    42.3 2016.81    57.8 2013.48    96.1 2007.71
   165.6 2001.07   187.7 1997.64   209.8 1992.82   309.2 1992.92   356.4 1989.83
     396  1989.8   430.6 1987.96   504.7 1987.02   515.5 1985.74     566 1984.29
   573.71982.814   586.2 1981.16   602.2 1981.51  612.24 1982.82   645.3 1989.31
   669.9 1987.58   712.8 1988.62   767.9 1995.86   842.7  1998.9   897.6 2003.68
   946.9 2015.16   997.3 2028.79  1052.1  2040.7    1073 2041.94  1077.5 2043.79
#Mann= 12 ,-1,0
       0     .07       0      50     .06       0      60     .05       0
     180     .06       0     200     .05       0     320     .06       0
     350      .1       0     460     .07       0     490      .1       0
   573.7    .045       0  612.24     .06       0  677.72      .1       0
Bank Sta=573.7,612.24
XS Rating Curve= 0 ,0
Exp/Cntr(USF)=0,0
Exp/Cntr=0.3,0.1
LCMann Table=0

Chan Stop Cuts=-1
Use User Specified Reach Order=0
Composite Channel Slope=5